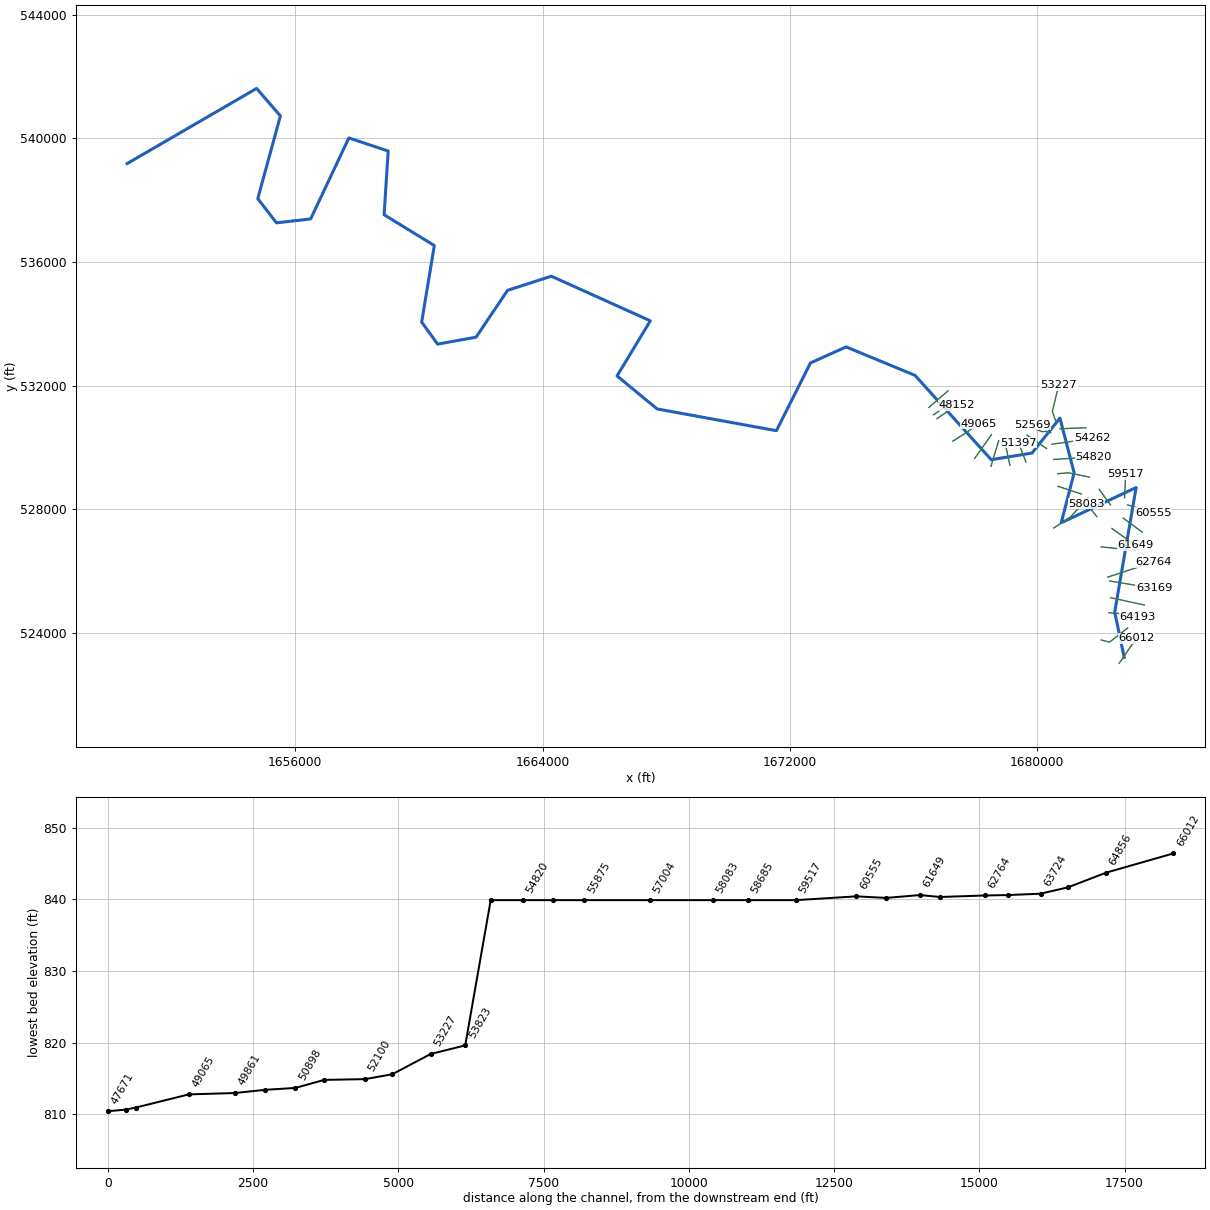
--- WhlingCk.prj (project) ---

Proj Title=WhlingCk
Current Plan=p01
Default Exp/Contr=0,0
English Units
Geom File=g01
Flow File=f01
Plan File=p01
BEGIN DESCRIPTION:
---------- MODELED AS PART OF WVEM CTP PROGRAM, 2025----------
Stream Name: Wheeling Creek
Flood Zone: AFH
Marshall County, WV
HEC-RAS Version: RAS 6.6
Vertical Datum: NAVD88
Projection: NAD 1983 StatePlane West Virginia N FIPS 4701 (US Feet)
Terrain: 1-meter West Virginia FEMA R3 South Central (collected 2018-2019)
Land Use: 2024 NLCD
Hydrologic Method:
Duda et al., "Estimation of magnitude and frequency of floods for rural, unregulated streams in and near Virginia and West Virginia." September 8, 2025.
Additional Model Notes:
Large dam near RS 54000
END DESCRIPTION:
DSS Export Rating Curves= 0
DSS Export Rating Curve Sorted= 0
DSS Export Volume Flow Curves= 0
DXF OffsetX= 0
DXF OffsetY= 0
DXF ScaleX= 0
DXF ScaleY= 0

--- WhlingCk.p01 (plan) ---

Plan Title=Floodplain
Program Version=6.60
Short Identifier=Floodplain
Geom File=g01
Flow File=f01
Subcritical Flow
K Sum by GR= 0
Std Step Tol= 0.01
Critical Tol= 0.01
Num of Std Step Trials= 20
Max Error Tol= 0.3
Flow Tol Ratio= 0.001
Split Flow NTrial= 30
Split Flow Tol= 0.02
Split Flow Ratio= 0.02
Log Output Level= 0
Friction Slope Method= 1
Unsteady Friction Slope Method= 2
Unsteady Bridges Friction Slope Method= 1
Parabolic Critical Depth
Global Vel Dist= 0 , 0 , 0
Global Log Level= 0
CheckData=False
Encroach Param=-1 ,0,0, 0
Flow Ratio Tolerance=0.1
Flow Ratio Min Ratio=0.5
Flow Ratio Max Ratio=4
Flow Ratio Max Iterations= 10
Mapping Interval=1HOUR
Computation Time Step Use Courant=        0
Computation Time Step Use Time Series=    0
Computation Time Step Count To Double=0
Computation Time Step Max Doubling=0
Computation Time Step Max Halving=0
Computation Time Step Residence Courant=0
Run HTab= 0
Run UNet= 0
Run Sediment= 0
Run PostProcess= 0
Run WQNet= 0
Run RASMapper=-1
UNET Theta= 0
UNET Theta Warmup= 0
UNET ZTol= 0
UNET ZSATol= 0
UNET MxIter= 0
UNET Max Iter WO Improvement= 0
UNET MaxInSteps= 0
UNET DtIC= 0
UNET DtMin= 0
UNET MaxCRTS= 0
UNET WFStab= 0
UNET SFStab= 0
UNET WFX= 1
UNET SFX= 1
UNET Gravity=32.17405
UNET 1D Methodology=Finite Difference
UNET DSS MLevel= 1
UNET Pardiso=0
UNET DZMax Abort= 0
UNET Use Existing IB Tables= 0
UNET Froude Reduction=False
UNET Froude Limit= 0
UNET Froude Power= 0
UNET D1 Cores= 0
UNET WindReference=Eulerian
UNET WindDragFormulation=Hsu (1988)
UNET D2 Coriolis=0
UNET D2 Cores= 0
UNET D2 Theta= 1
UNET D2 Theta Warmup= 1
UNET D2 Z Tol= 0.01
UNET D2 Volume Tol= 0.01
UNET D2 Max Iterations= 20
UNET D2 Advanced Convergence=0
UNET D2 WS Max Tol=0.15
UNET D2 WS RMS Tol=0.002
UNET D2 WS Stall Tol=1
UNET D2 Equation= 0
UNET D2 RampUpFraction=0.1
UNET D2 TimeSlices= 1
UNET D2 Turbulence Formulation=Non-Conservative (original)
UNET D2 Eddy Viscosity=0.3
UNET D2 Transverse Eddy Viscosity=0.1
UNET D2 Smagorinsky Mixing=0
UNET D2 BCVolumeCheck=0
UNET D2 Cores=0
UNET D2 SolverType=PARDISO (Direct)
UNET D2 Minimum Iterations= 3
UNET D2 Maximum Iterations= 30
UNET D2 Restart Number= 10
UNET D2 Relaxation Coeff=1.3
UNET D2 SOR Precondition Iterations= 10
UNET D2 ILUT Maximum Fill= 8
UNET D2 ILUT Tolerance=1E-08
UNET D2 Convergence Tolerance=0.00001
PS Theta= 1
PS WS Tol= 0.01
PS Volume Tol= 0.01
PS Max Iterations= 20
PS Equation= 0
PS Advance Time Step=-1
PS Target Courant=0.9
PS Time Slices= 1
PS Iterate With 2D=0
PS Project Initial WSE from DS=-1
PS Ramp Up Initial WSE from US=-1
PS Cores=0
UNET D1D2 MaxIter= 0
UNET D1D2 ZTol=0.01
UNET D1D2 QTol=0.1
UNET D1D2 MinQTol=1
Write IC File= 0
Write IC File at Fixed DateTime=0
Write IC File at Sim End=0
Echo Input=False
Echo Parameters=False
Echo Output=False
Write Detailed= 0
HDF Write Warmup=0
HDF Write Time Slices=0
HDF Flush=0
HDF Compression= 1
HDF Chunk Size= 1
HDF Spatial Parts= 1
HDF Use Max Rows=0
HDF Fixed Rows= 1
Calibration Method= 0
Calibration Iterations= 20
Calibration Max Change=0.05
Calibration Tolerance=0.2
Calibration Maximum=1.5
Calibration Minimum=0.5
Calibration Optimization Method= 1
WQ AD Non Conservative
WQ ULTIMATE=-1
WQ Max Comp Step=1HOUR
WQ Output Interval=15MIN
WQ Output Selected Increments= 0
WQ Create Restart=0
WQ Fixed Restart=0
WQ System Summary=0
WQ Write To DSS=0
Sorting and Armoring Iterations= 10
XS Update Threshold= 0.02
Bed Roughness Predictor= 0
Processes Affected by Predictor=Sediment Only
Hydraulics Update Threshold= 0.02
Energy Slope Method= 1
Volume Change Method= 1
Sediment Retention Method= 0
Sediment TS Multiplier= 1
Warm Up Method= 0
XS Weighting Method= 0
Number of US Weighted Cross Sections= 1
Number of DS Weighted Cross Sections= 1
Upstream XS Weight=0
Main XS Weight=1
Downstream XS Weight=0
Number of DS XS's Weighted with US Boundary= 1
Upstream Boundary Weight= 1
Weight of XSs Associated with US Boundary= 0
Number of US XS's Weighted with DS Boundary= 1
Downstream Boundary Weight= 0.5
Weight of XSs Associated with DS Boundary= 0.5
Percentile Method= 0
Sediment Output Level= 3
Mass or Volume Output= 0
Output Increment Type= 1
Profile and TS Output Increment= 1
Transport Output Increment 1
XS Output Flag= 0
XS Output Increment= 10
Read HDF5 Sediment Hotstart= 0
Sediment Hotstart Type= 0
Write Gradation File= 0
Read Gradation Hotstart= 0
Write HDF5 File= 1
Write Binary Output= 1
Write DSS Sediment File= 0
DSS Sediment Output Type= 1
SV Curve= 0
Specific Gage Flag= 0
Subcell Erosion Methods= 0
Subcell Deposition Methods= 0
Advection Scheme= 1
Matrix Solver= 0
Implicit Weighting Factor= 1
Maximum Outer Loop Convergence Iterations= 5
Convergence Maximum Absolute= 0.001
Convergence RMSE= 0.0001
Grain Fractions Max Abs Error= 0.001
Max Subgrid Regions= 1
Max Subgrid Length Scale= 3.402823E+38
Initial Layer Thickness= 3
Min Layer Thickness= 0.1
Max Layer Thickness= 6
Number of Layers= 5

--- WhlingCk.f01 (steady flow) ---

Flow Title=Flow
Program Version=6.60
Number of Profiles= 1
Profile Names=P100yr
River Rch & RM=WhlingCk,Main            ,66012
   14100
River Rch & RM=WhlingCk,Main            ,35656
   16200
Boundary for River Rch & Prof#=WhlingCk,Main            , 1
Up Type= 0
Dn Type= 1
Dn Known WS=761.2
DSS Import GetInterval= 0
DSS Import GetPeak= 0
DSS Import FillOption= 0

--- WhlingCk.g01 (geometry) ---

Geom Title=Geometry
Program Version=6.60

River Reach=WhlingCk        ,Main
Reach XY= 30
1682814.34458643 523204.40061066     1682507.537      524666.578
     1683201.089      528699.778     1680777.185      527558.234
     1681195.965      529175.624     1680735.483      530948.308
1679831.26764483529814.775967252     1678512.741      529601.113
     1676047.786      532329.9951673818.53531767533251.965668905
     1672664.864      532732.761     1671563.103      530539.786
     1667704.425      531243.531     1666407.412       532312.46
     1667484.619      534096.414     1664280.682      535541.302
     1662864.989      535083.472      1661845.96      533566.171
      1660601.46      533342.656     1660087.134      534056.889
     1660495.695      536534.332     1658871.864      537529.573
     1659003.719      539593.156     1657731.915      540017.448
1656494.62401732537394.271228165     1655389.062      537268.756
 1654784.3286284538052.709743194     1655516.473      540730.345
     1654745.906      541619.3951650558.04678915539186.766592096

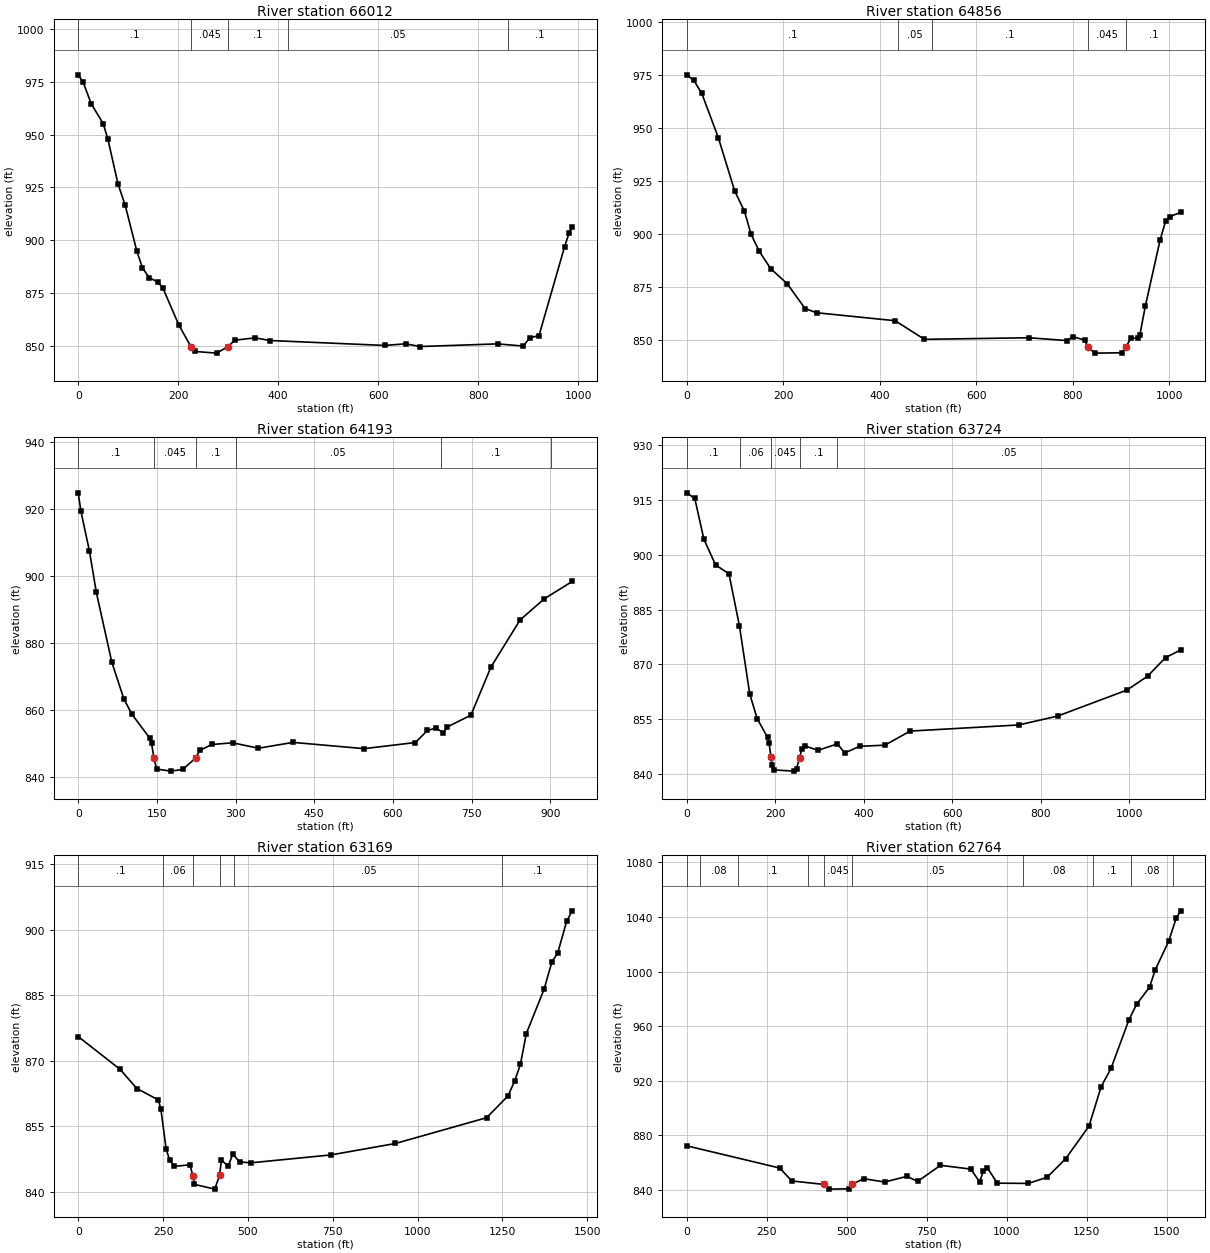
Type RM Length L Ch R = 1 ,66012   ,1132.5,1156.1,1111.6
XS GIS Cut Line= 2
 1682652.3224211 523010.166091781683212.90607887523823.903163142
#Sta/Elev= 30
       0  978.42      10  974.84      26  964.66    49.9  955.27    59.1  948.11
    79.6  926.61    93.8  916.67   117.3  894.69   128.5  886.87   141.5  882.27
   159.8  880.03   169.4  877.26   201.3  859.68  225.77849.3465   233.1  847.19
   276.9   846.4  299.61 849.483   313.1  852.53     354  853.65   382.9  852.39
   612.7  850.05   655.1  850.81   683.3  849.53   838.7  850.78   890.5  849.75
   902.8  853.61   921.7  854.74   972.8  896.82   982.1  903.54   988.1  906.29
#Mann= 5 ,-1,0
       0      .1       0  225.77    .045       0  299.61      .1       0
     420     .05       0     860      .1       0
Bank Sta=225.77,299.61
XS Rating Curve= 0 ,0
Exp/Cntr=0.3,0.1

Type RM Length L Ch R = 1 ,64856   ,692.5,662.4,636.4
XS GIS Cut Line= 3
1682071.45196347523764.0671039771682339.82962378523692.702307834
1682927.17163404524152.463466038
#Sta/Elev= 30
       0  974.95    14.5  972.34      31  966.28    65.4  945.31    99.4  920.13
   119.5  910.66   133.3  899.74   150.3  891.69   174.1  883.51   208.1  876.45
   245.3  864.72   269.1  862.76   431.8     859   492.6  850.22   708.8  850.97
     787  849.65   800.5  851.45   824.4  849.88  831.88846.4202   845.5  843.72
   901.6  843.88  909.87 846.562   920.3  850.75   934.3  850.78     939  852.43
   950.4  866.04     981  897.19   992.1  905.79  1000.4  908.07  1023.6  910.09
#Mann= 5 ,-1,0
       0      .1       0   437.7     .05       0   507.7      .1       0
  831.88    .045       0  909.87      .1       0
Bank Sta=831.88,909.87
XS Rating Curve= 0 ,0
Exp/Cntr(USF)=0,0
Exp/Cntr=0.3,0.1

Type RM Length L Ch R = 1 ,64193   ,473.3,468.8,463.9
XS GIS Cut Line= 3
1682320.07362062524645.3895111051682999.71930739524596.563679729
1683244.58302331524507.236011489
#Sta/Elev= 30
       0  924.86     4.9  919.52    21.3   907.5    34.5  895.11    64.1  874.19
    87.1  863.22   102.5  858.64   136.5  851.49   139.8     850  144.44 845.472
   149.6  842.29   176.1  841.66     199  842.15   223.8845.5481   231.9  847.87
   254.9  849.63   294.4  850.12   343.7  848.51   409.6  850.25   545.1  848.38
     643  850.21     666  853.83   682.6  854.53   696.5  853.06   703.5  854.85
   748.9  858.39   786.9  872.73   842.5  886.83   888.6  893.16     942  898.36
#Mann= 6 ,-1,0
       0      .1       0  144.44    .045       0   223.8      .1       0
     300     .05       0   691.4      .1       0   901.4     .05       0
Bank Sta=144.44,223.8
XS Rating Curve= 0 ,0
Exp/Cntr(USF)=0,0
Exp/Cntr=0.3,0.1

Type RM Length L Ch R = 1 ,63724   ,544.8,555.8,554.6
XS GIS Cut Line= 2
1682376.04725436525133.2788110551683467.39480096 524895.79124194
#Sta/Elev= 30
       0  916.94    18.2   915.4    38.7  904.24    65.2  897.21    95.4  894.78
     119  880.59   142.5  861.85   159.2  855.15   182.7  850.02   186.1  848.47
   190.4  844.58   192.8  842.37   196.2  841.12   243.2  840.78   248.3  841.49
  255.26844.4882     260  846.72   266.7   847.7   296.9  846.48   340.6  848.24
   357.3  845.76   390.9  847.57     448  847.88   505.1  851.74   750.2  853.41
   838.4  855.84   995.3  862.96    1042  866.75  1082.6  871.86  1116.9  873.94
#Mann= 5 ,-1,0
       0      .1       0     120     .06       0   190.4    .045       0
  255.26      .1       0     340     .05       0
Bank Sta=190.4,255.26
XS Rating Curve= 0 ,0
Exp/Cntr(USF)=0,0
Exp/Cntr=0.3,0.1

Type RM Length L Ch R = 1 ,63169   ,335.2,404.3,389.9
XS GIS Cut Line= 2
 1682344.7510994525673.4307482361683781.27534963525438.192060971
#Sta/Elev= 30
       0  875.51   122.9  868.04   172.8  863.62   235.9  861.02   243.5  858.92
   259.2   849.7   269.1  847.35   282.5  845.79     329  846.16  337.76  843.69
   342.3  841.68   402.2  840.59   416.3  843.71   422.1  847.23     442  845.83
   455.3  848.63   475.3  846.82   508.5  846.61   744.6  848.42   934.8  851.04
  1203.4  856.94  1266.5  861.93  1286.5   865.4  1303.1  869.16  1320.4  876.18
  1372.9  886.37  1396.2  892.69  1412.8   894.6  1439.4  901.91  1455.7   904.3
#Mann= 6 ,-1,0
       0      .1       0     250     .06       0  337.76    .045       0
   416.3      .1       0     460     .05       0    1250      .1       0
Bank Sta=337.76,416.3
XS Rating Curve= 0 ,0
Exp/Cntr(USF)=0,0
Exp/Cntr=0.3,0.1

Type RM Length L Ch R = 1 ,62764   ,783.3,771,750
XS GIS Cut Line= 2
 1682282.0207828525798.8913814431683748.90340847 526281.14037094
#Sta/Elev= 30
       0  872.28   290.4  856.01   328.4  846.51   428.4843.9906     446  840.53
     508  840.76   516.2  844.02   552.9   848.2   618.5  845.72   687.6  849.85
   722.1  846.26   793.1  857.99     888   855.2   915.5  845.82   926.8  853.51
   939.7  856.13   970.7  844.91  1067.2  844.71  1126.2  849.17  1184.9  862.95
  1257.4  886.75  1295.4  915.64  1326.5   929.2  1381.6  964.23  1405.9  975.92
  1446.6  988.53  1464.6 1001.35  1506.4 1022.15  1530.2 1039.33  1544.1 1044.53
#Mann= 10 ,-1,0
       0      .1       0      40     .08       0     160      .1       0
     380     .06       0   428.4    .045       0   516.2     .05       0
    1050     .08       0    1270      .1       0    1390     .08       0
    1520      .1       0
Bank Sta=428.4,516.2
XS Rating Curve= 0 ,0
Exp/Cntr(USF)=0,0
Exp/Cntr=0.3,0.1

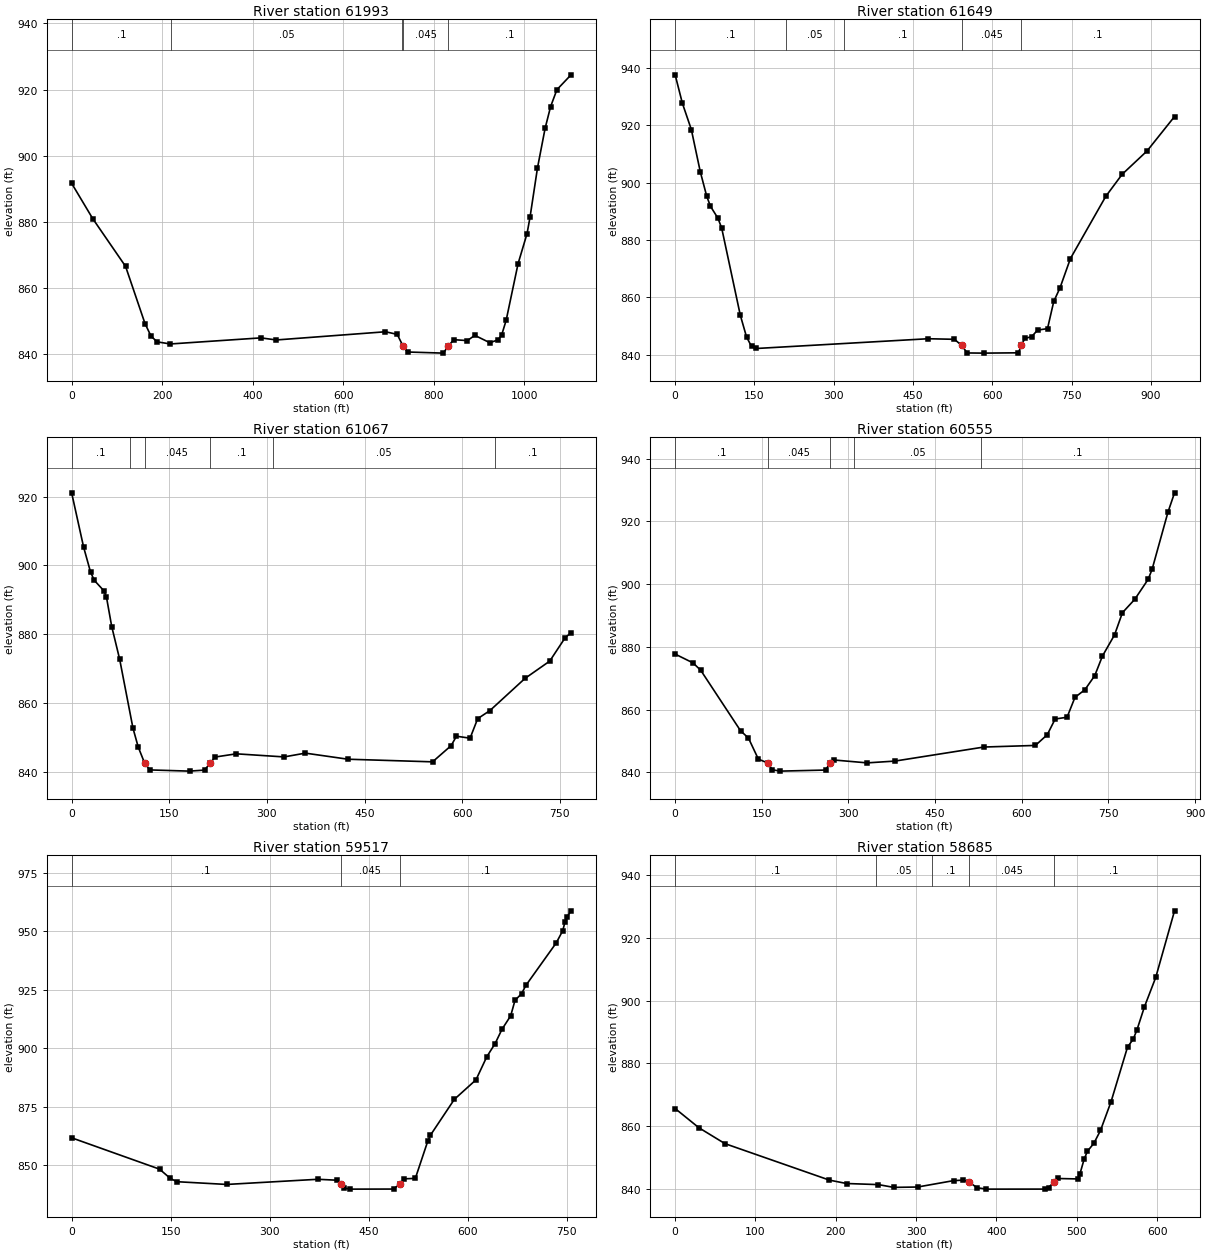
Type RM Length L Ch R = 1 ,61993   ,361.1,344,305
XS GIS Cut Line= 2
1682071.87422218526777.4843204641683169.65476274526664.569750577
#Sta/Elev= 30
       0  891.65    46.6  880.98   119.2  866.54   162.1  849.27   175.3   845.5
   188.8  843.73   218.1  843.09   418.4  844.93   452.3   844.3   693.6  846.78
   719.5  845.99  732.84842.3268   742.5  840.66   821.7  840.32   831.6   842.4
   844.8  844.38   874.5  844.11     891  845.69   924.1  843.47   942.5  844.34
   950.3   845.8   960.2  850.21   986.6  867.37  1006.4  876.45    1013  881.41
  1029.5  896.33  1046.4  908.32  1058.4  914.81  1072.4  919.96  1103.6  924.45
#Mann= 5 ,-1,0
       0      .1       0     220     .05       0     730      .1       0
  732.84    .045       0   831.6      .1       0
Bank Sta=732.84,831.6
XS Rating Curve= 0 ,0
Exp/Cntr(USF)=0,0
Exp/Cntr=0.3,0.1

Type RM Length L Ch R = 1 ,61649   ,596.5,582.3,600.2
XS GIS Cut Line= 2
 1682416.8909635527373.422328201 1683185.3373419526824.532057917
#Sta/Elev= 30
       0  937.66    13.7  927.73    30.6  918.58    47.5  903.88    59.7  895.32
    66.8   891.8    80.9  887.65      88  884.22   123.2  853.82     135  846.23
   144.4  842.92   153.8  842.21   478.4  845.61   528.1  845.41  541.82843.2769
   552.3  840.65   583.8  840.59     649   840.7   654.8  843.37   661.1   845.7
   674.1  846.33   685.2  848.61   704.1  849.14   715.9  858.61   727.7  863.34
   747.4  873.57   814.3  895.27   845.3  902.97   892.3   911.1   944.3  923.11
#Mann= 5 ,-1,0
       0      .1       0     210     .05       0     320      .1       0
  541.82    .045       0   654.8      .1       0
Bank Sta=541.82,654.8
XS Rating Curve= 0 ,0
Exp/Cntr(USF)=0,0
Exp/Cntr=0.3,0.1

Type RM Length L Ch R = 1 ,61067   ,491.8,511.7,526.7
XS GIS Cut Line= 2
1682783.86331563527709.0295220321683401.75693418527254.234726654
#Sta/Elev= 30
       0  921.08    18.4   905.3      29  898.08    34.8  895.64    49.4  892.64
    53.5  890.77    61.6  882.21    73.8  872.69    94.2   852.7   102.3  847.19
  112.03842.5673   120.2  840.54   181.1  840.19   204.2  840.49  212.74842.4955
   220.5  844.29     253  845.22   326.4  844.32     359  845.42   424.6  843.65
   554.5  842.89     583   847.6   591.2  850.34   612.1  849.76   623.8  855.44
   642.6  857.79   696.5  867.14   734.5  872.17   758.2  878.97   767.2  880.44
#Mann= 6 ,-1,0
       0      .1       0      90     .06       0  112.03    .045       0
  212.74      .1       0     310     .05       0     650      .1       0
Bank Sta=112.03,212.74
XS Rating Curve= 0 ,0
Exp/Cntr(USF)=0,0
Exp/Cntr=0.3,0.1

Type RM Length L Ch R = 1 ,60555   ,979.4,1038.6,1148
XS GIS Cut Line= 2
1682921.87001216528135.5956749381683749.91019133527887.810924353
#Sta/Elev= 30
       0  877.72      31   874.9    44.3  872.55   113.2  853.28   126.9  850.94
     144  844.24   161.2  842.94     168  840.85   181.3  840.41   260.5  840.75
  267.95     843   274.2  843.97   332.4  843.04   380.3  843.61   534.4  848.09
   623.5   848.6     644  852.01   657.7  857.02   678.3  857.59     692  863.93
   709.1  866.34   726.2  870.84   739.5  877.08   760.5  883.85   774.1  890.91
   795.5  895.18   818.7  901.56   825.5  904.76   852.9  922.94   864.3  929.12
#Mann= 5 ,-1,0
       0      .1       0   161.2    .045       0  267.95      .1       0
     310     .05       0     530      .1       0
Bank Sta=161.2,267.95
XS Rating Curve= 0 ,0
Exp/Cntr(USF)=0,0
Exp/Cntr=0.3,0.1

Type RM Length L Ch R = 1 ,59517   ,802.3,831.6,864.9
XS GIS Cut Line= 2
1682827.77453725528370.8343622031682862.27621139 529126.73467728
#Sta/Elev= 30
       0  861.79   133.2  848.41   149.6  844.44   159.5  843.05     235  841.88
     373  844.08   402.5  843.68  407.79 842.002   412.4  840.35   421.8  839.88
   487.9  839.91   497.2  842.05   504.3  844.28   520.8  844.47   539.7  860.42
   543.7  862.91   579.9  878.21   612.7  886.55   629.1  896.41   641.7  902.04
   652.1  908.12   665.3  913.89   671.8  920.47   681.7   923.3   688.3  926.86
   734.2  944.96   744.1  950.17   747.4  953.76   750.7   956.1   756.7  958.69
#Mann= 3 ,-1,0
       0      .1       0  407.79    .045       0   497.2      .1       0
Bank Sta=407.79,497.2
XS Rating Curve= 0 ,0
Exp/Cntr(USF)=0,0
Exp/Cntr=0.3,0.1

Type RM Length L Ch R = 1 ,58685   ,599.5,602.5,604.2
XS GIS Cut Line= 2
1682372.97974188528135.5956749381682006.00738974 528637.43820777
#Sta/Elev= 30
       0  865.59    29.5  859.47      62  854.39   192.1  842.75   213.4  841.67
   253.1  841.32   272.1  840.44   301.8  840.55   346.6  842.59   358.7  842.75
     366  842.13   375.9  840.32   387.6  839.88   460.4  839.89   464.9  840.36
  471.53842.1642   476.6  843.27     501  843.13   503.8  844.61   509.1  849.39
   513.2  851.94   521.3  854.51   529.5  858.59   542.7  867.79   563.2   885.2
   570.3  887.73     575  890.74   584.3  898.08   598.3  907.41   621.7  928.65
#Mann= 5 ,-1,0
       0      .1       0     250     .05       0     320      .1       0
     366    .045       0  471.53      .1       0
Bank Sta=366,471.53
XS Rating Curve= 0 ,0
Exp/Cntr(USF)=0,0
Exp/Cntr=0.3,0.1

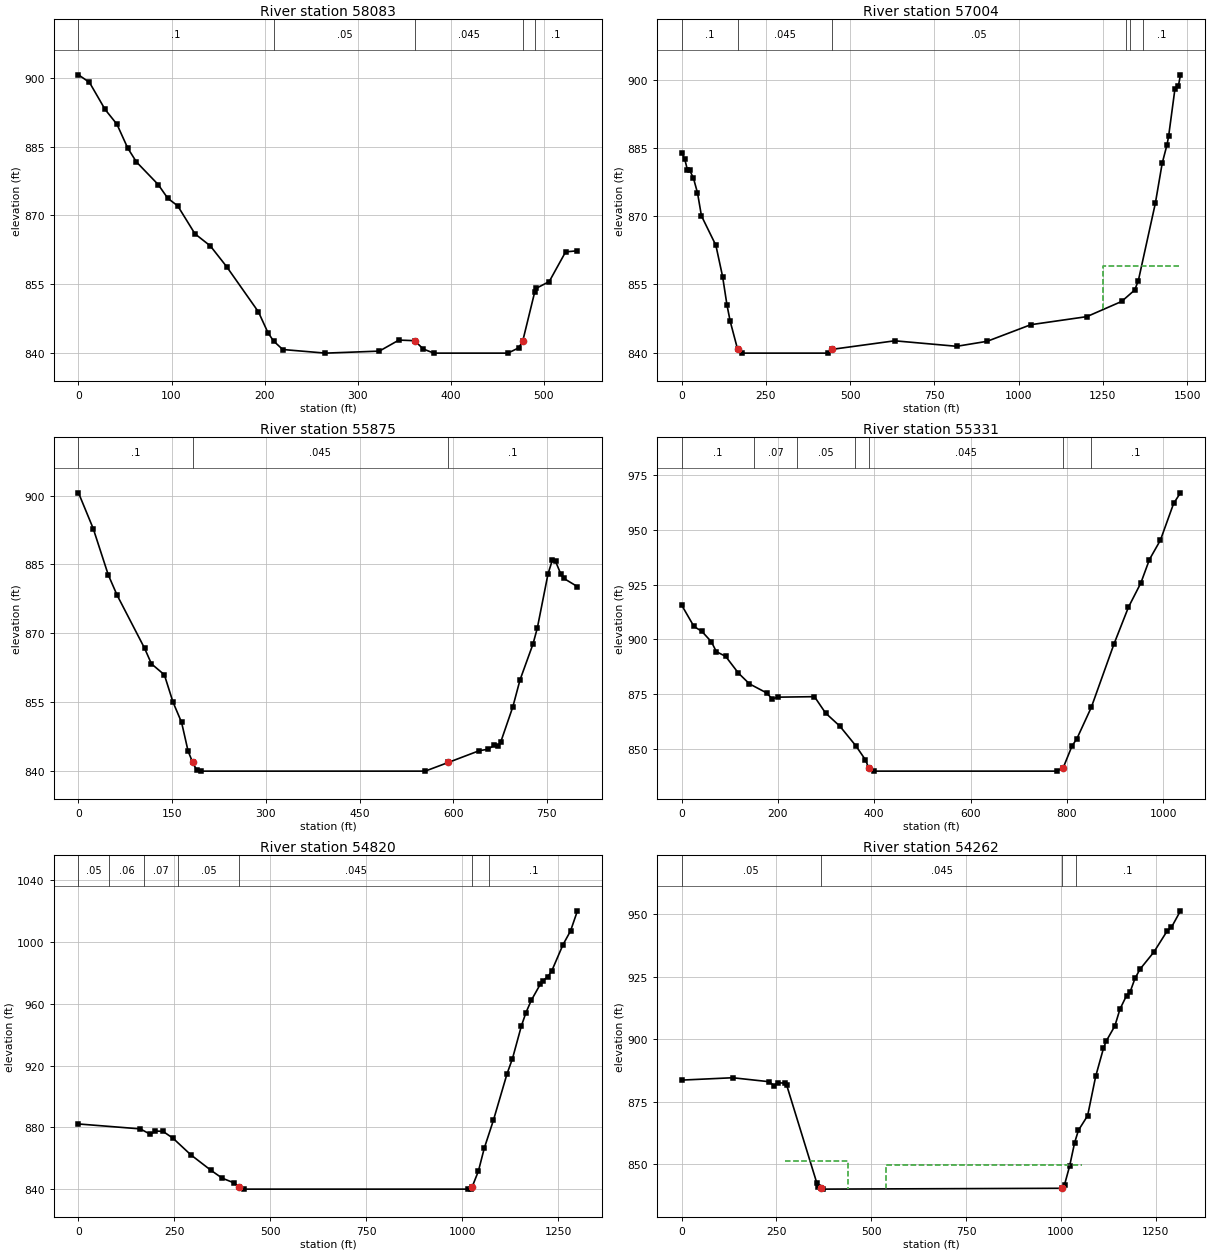
Type RM Length L Ch R = 1 ,58083   ,1252.2,1078.7,892.4
XS GIS Cut Line= 2
1681927.61475728527759.8432991351681591.93770383 528177.73131495
#Sta/Elev= 30
       0  900.66    11.8     899    28.6  893.09    41.3  889.87    52.9  884.66
    62.3  881.62    85.6   876.7    95.9   873.7   106.6  872.04   125.1  865.94
   141.6   863.3   159.1  858.78   193.3  848.89   203.7  844.28   209.6  842.52
   219.4  840.67   265.3  839.88   323.2  840.32   344.2  842.73  361.21 842.595
   370.3  840.78   381.8  839.88   461.3  839.88     473  841.04  477.25 842.535
     490  853.14   491.9  854.05   505.7  855.51   523.3  861.99     536  862.23
#Mann= 5 ,-1,0
       0      .1       0     210     .05       0  361.21    .045       0
  477.25     .05       0     490      .1       0
Bank Sta=361.21,477.25
XS Rating Curve= 0 ,0
Exp/Cntr(USF)=0,0
Exp/Cntr=0.3,0.1

Type RM Length L Ch R = 1 ,57004   ,1236.3,1128.7,982.5
XS GIS Cut Line= 3
1680536.74986263527388.6532490731681062.64947188527733.917775145
1681643.42556209528355.851226082
#Sta/Elev= 30
       0  883.97     9.5  882.54    17.6  880.12    23.8  880.15    35.5  878.31
    47.4  875.11    59.1  870.05   101.9  863.58   121.9   856.7     135  850.39
   144.5  846.85  166.35840.7267     179  839.88     436  839.88   447.6  840.72
   632.5  842.59   816.3  841.38   906.7  842.48  1036.2  846.13  1202.3   847.9
  1305.6  851.24  1344.2  853.74    1355  855.78  1405.5  872.79  1425.9  881.61
  1440.3  885.72  1444.9  887.53  1463.5  897.84    1474  898.64  1480.1  901.05
#Mann= 6 ,-1,0
       0      .1       0  166.35    .045       0   447.6     .05       0
 1319.11      .1       0 1329.11     .05       0 1369.11      .1       0
#XS Ineff= 2 , 0
                         1251.12          859.05
Permanent Ineff=
       F       F
Bank Sta=166.35,447.6
XS Rating Curve= 0 ,0
Exp/Cntr(USF)=0,0
Exp/Cntr=0.3,0.1

Type RM Length L Ch R = 1 ,55875   ,528.3,544.6,573.3
XS GIS Cut Line= 2
1680668.71955345528739.8730760571681428.07003594528491.461022305
#Sta/Elev= 30
       0  900.59    23.6  892.79    47.7  882.69    61.8  878.27     106  866.64
   116.8  863.29   137.5   860.9   151.3  854.95   165.1  850.51   175.5  844.25
   182.9841.7631   189.2  840.13   196.2  839.88   555.2  839.88  591.99841.7632
   641.8  844.34   655.3  844.64   665.6  845.48   672.5  845.33     676  846.16
   695.6  853.93     707  859.76   727.8   867.6   734.7  871.06   751.9  882.91
   758.8  885.91     764  885.62   772.6   882.8     777  881.94     799  880.13
#Mann= 3 ,-1,0
       0      .1       0   182.9    .045       0  591.99      .1       0
Bank Sta=182.9,591.99
XS Rating Curve= 0 ,0
Exp/Cntr(USF)=0,0
Exp/Cntr=0.3,0.1

Type RM Length L Ch R = 1 ,55331   ,479.3,510.7,595.3
XS GIS Cut Line= 3
1680665.40246719529147.1681431951681013.45272174529175.735095237
1681685.92769003529037.514048515
#Sta/Elev= 30
       0  915.78    25.8  905.93    42.3  903.67      62  898.93    72.3  894.42
    91.6  892.28     118  884.66     141  879.72   177.2  875.53   187.9  872.87
   200.3  873.65     276  873.87     299  866.41   328.7  860.41   361.8  851.47
   381.9  845.01  388.32841.5007   398.6  839.88   778.5  839.88  792.53841.5012
   810.6  851.34   820.7  854.66   850.7     869   897.7  897.87   927.8  914.71
   953.6   925.8   971.4  936.49   994.2  945.34  1021.6  962.08  1035.8  966.93
#Mann= 7 ,-1,0
       0      .1       0     150     .07       0     240     .05       0
  359.22    .025       0  388.32    .045       0  792.53    .025       0
  849.22      .1       0
Bank Sta=388.32,792.53
XS Rating Curve= 0 ,0
Exp/Cntr(USF)=0,0
Exp/Cntr=0.3,0.1

Type RM Length L Ch R = 1 ,54820   ,531.4,558.2,581.1
XS GIS Cut Line= 2
1680530.55964014529609.8192618841681827.81404447529688.782573452
#Sta/Elev= 30
       0  882.12   160.9  878.93   187.2  875.41   200.3  877.52     220  877.34
   246.3  872.86   292.3  862.19   344.9  852.11   374.4  846.97   404.1  844.03
  418.49841.2399   430.2  839.88  1015.8  839.88    1022  840.12 1025.28 841.241
  1041.7  851.54    1057   866.4  1080.9  884.59  1116.5  914.79  1130.5  924.51
  1153.5   945.5  1165.5  954.26  1179.5  962.27  1202.8  972.62  1209.4  974.94
  1222.5  977.49  1232.7  981.27    1262   998.3  1281.7 1007.22  1299.7 1020.28
#Mann= 7 ,-1,0
       0     .05       0      80     .06       0     170     .07       0
     260     .05       0  418.49    .045       0 1025.28    .025       0
    1070      .1       0
Bank Sta=418.49,1025.28
XS Rating Curve= 0 ,0
Exp/Cntr(USF)=0,0
Exp/Cntr=0.3,0.1

Type RM Length L Ch R = 1 ,54262   ,464.5,438.4,658.2
XS GIS Cut Line= 2
1680478.86075338530101.2265893061681780.85349685 530288.38804618
#Sta/Elev= 30
       0  883.58   134.9  884.53     231  882.94   244.3  881.32   254.2  882.48
   274.1  882.39   277.4  881.48     357  842.18   360.3  840.79  367.71840.2169
   373.8  839.88 1003.24840.2161  1009.9  841.72  1023.2  849.14  1036.4  858.53
  1046.4  863.47  1070.6  869.31    1092  885.17  1112.3  896.27  1119.3  899.12
  1142.5  905.31  1155.8  912.01  1173.2  917.45  1182.3  918.79  1195.5  924.35
  1208.8  928.06  1245.3  934.91  1280.4  943.39  1291.7  944.84  1315.4  951.44
#Mann= 4 ,-1,0
       0     .05       0  367.71    .045       0 1003.24    .025       0
    1040      .1       0
#XS Ineff= 2 ,-1
  271.91   438.7  851.09  538.77 1056.32849.7167
Permanent Ineff=
       F       F
Bank Sta=367.71,1003.24
XS Rating Curve= 0 ,0
Exp/Cntr(USF)=0,0
Exp/Cntr=0.3,0.1

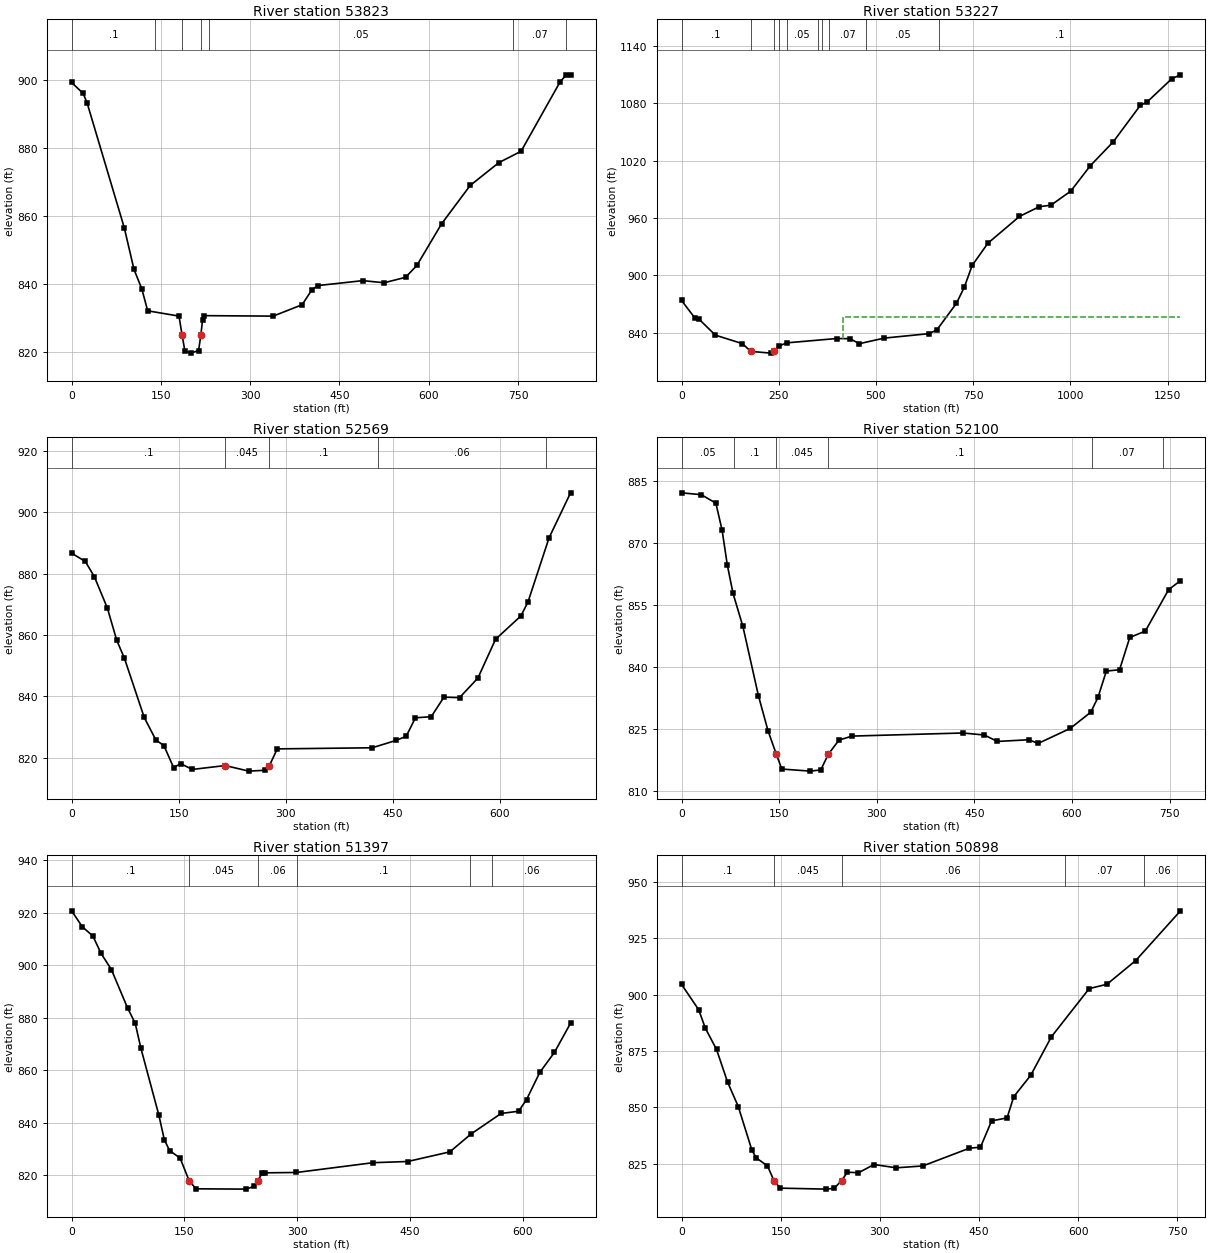
Type RM Length L Ch R = 1 ,53823   ,554.1,596.7,644.1
XS GIS Cut Line= 3
1680734.08243172530598.2858855321681014.57886159530614.417293838
1681571.50053426530632.659214699
#Sta/Elev= 30
       0  899.19    19.4  895.97      26  893.19    88.4  856.52   104.8  844.24
     118  838.47   127.8  832.06   180.4  830.51  185.44825.0718   190.3  820.25
   200.1  819.62   213.3  820.37  217.22825.0768   219.9   829.3   223.2  830.64
   338.6   830.5   387.3  833.85   403.8  838.28   413.6  839.48   489.1  840.93
   525.2  840.31     561  841.91   580.1  845.42   621.4  857.61   669.6  868.92
   717.7  875.62   755.1  878.97   820.6  899.36   830.5  901.32   838.2  901.44
#Mann= 7 ,-1,0
       0      .1       0     140     .06       0  185.44    .045       0
  217.22     .06       0     230     .05       0  740.96     .07       0
  830.96     .06       0
Bank Sta=185.44,217.22
XS Rating Curve= 0 ,0
Exp/Cntr(USF)=0,0
Exp/Cntr=0.3,0.1

Type RM Length L Ch R = 1 ,53227   ,602.2,657.5,686.1
XS GIS Cut Line= 3
1680628.09122834530767.3424854961680491.38199028531167.705254114
  1680694.549342532003.181322246
#Sta/Elev= 30
       0  873.63      35  854.83    45.4  853.84      87  837.25   156.4  828.36
  178.15820.2394   229.2  818.41  238.95820.2407     250  825.82   270.8  829.17
     399  833.72   433.4  833.51   457.1  828.29   521.2  834.15     636  838.78
   656.3  842.59   706.9   870.6   727.3  887.67   747.4  910.32   787.9  933.57
     869  961.56   919.6  971.73     950  973.37  1000.7  988.04  1051.3 1014.76
  1110.1 1039.69  1179.6 1077.88    1197 1081.36  1260.6 1105.78  1282.9 1109.87
#Mann= 10 ,-1,0
       0      .1       0  178.15    .045       0  238.95      .1       0
     250     .06       0     270     .05       0     350     .07       0
     360     .05       0     380     .07       0  473.06     .05       0
  663.06      .1       0
#XS Ineff= 2 , 0
                          414.44          855.73
Permanent Ineff=
       F       F
Bank Sta=178.15,238.95
XS Rating Curve= 0 ,0
Exp/Cntr(USF)=0,0
Exp/Cntr=0.3,0.1

Type RM Length L Ch R = 1 ,52569   ,488.3,469.3,436
XS GIS Cut Line= 5
1680437.08878065530476.8748080531680303.23450445530519.123040277
1680165.11069072530507.8934619251679961.93926036530579.457339423
1679828.87444996530735.251572598
#Sta/Elev= 30
       0  886.63    19.2  883.93    31.9  878.95    50.1  868.74    63.3  858.18
    73.8  852.52   101.7  833.11   118.2  825.69   129.3  823.93   142.9  816.76
   152.8  818.02   169.2  816.14   215.3  817.41   248.2  815.59   271.3  815.87
  277.07  817.34   288.2  822.84   421.2   823.2   455.2  825.64   468.9  826.96
   481.8  832.97   503.9  833.33   521.8   839.7   543.6  839.54   569.3  845.91
   594.1  858.57   629.6  866.17   639.5  870.71   669.1  891.65   699.2   906.3
#Mann= 5 ,-1,0
       0      .1       0   215.3    .045       0  277.07      .1       0
  428.94     .06       0  664.35      .1       0
Bank Sta=215.3,277.07
XS Rating Curve= 0 ,0
Exp/Cntr(USF)=0,0
Exp/Cntr=0.3,0.1

Type RM Length L Ch R = 1 ,52100   ,723.7,703.2,674.2
XS GIS Cut Line= 2
1680302.76565069529961.4371784261679672.30001018530397.737676021
#Sta/Elev= 30
       0  882.04    30.4  881.59    52.8  879.55    62.4  872.99    70.3  864.69
    79.2  857.76    94.3  849.82   118.2  833.09   132.9  824.65  145.65818.9943
   154.1  815.41     198  814.91     214  815.21  225.64818.9924   241.9  822.38
   261.8  823.36   432.4  824.11   465.4  823.62   485.3  822.07   533.8  822.48
   547.9  821.58   597.4  825.22   628.9  829.13   639.9  832.69   652.8  839.04
   673.1  839.37   688.8  847.15   712.7  848.69   748.6   858.7   766.7  860.85
#Mann= 6 ,-1,0
       0     .05       0      80      .1       0  145.65    .045       0
  225.64      .1       0     630     .07       0     740     .06       0
Bank Sta=145.65,225.64
XS Rating Curve= 0 ,0
Exp/Cntr(USF)=0,0
Exp/Cntr=0.3,0.1

Type RM Length L Ch R = 1 ,51397   ,505.4,498.4,491.2
XS GIS Cut Line= 2
 1679635.7512774 529527.420976631679395.90021851 530146.46513814
#Sta/Elev= 30
       0  920.77    14.2  914.71    28.3  911.17    39.2  904.54    52.9  898.42
    74.4  883.82    84.6  877.97    92.2  868.43   116.2  842.84   123.3  833.66
   130.3   829.5   144.4   826.6   156.4817.9694   165.5  814.92   232.3   814.8
   242.9  815.88  247.61817.9692   253.4  820.79     257     821   299.2  821.14
   401.2  824.87   447.2  825.32   503.3  828.99   531.4  835.78   571.5  843.62
   594.7  844.45   605.3  848.87   622.9  859.22   642.5  866.89   663.9     878
#Mann= 6 ,-1,0
       0      .1       0   156.4    .045       0  247.61     .06       0
     300      .1       0     530     .05       0     560     .06       0
Bank Sta=156.4,247.61
XS Rating Curve= 0 ,0
Exp/Cntr(USF)=0,0
Exp/Cntr=0.3,0.1

Type RM Length L Ch R = 1 ,50898   ,539.5,515.4,487.6
XS GIS Cut Line= 2
1679117.21613105529420.0590740811678959.59972092530157.886617134
#Sta/Elev= 30
       0  904.57      26  893.28      36  885.12    52.9   875.7    69.6  861.22
    85.8  850.35   106.5  830.91   113.2  827.49     130     824  139.84817.4066
   149.3  814.12   218.5  813.68   230.7  814.03  241.93817.4095   250.8  821.19
   267.6  820.95   291.1  824.61   324.6  823.14   364.9  823.97   435.3  831.84
   452.1   832.3   468.9  843.97   492.3   845.3   502.4  854.71   528.1  864.21
   559.4  881.33   616.5  902.69   643.3   904.6   686.9  915.15   754.5   937.2
#Mann= 5 ,-1,0
       0      .1       0  139.84    .045       0  241.93     .06       0
     580     .07       0     700     .06       0
Bank Sta=139.84,241.93
XS Rating Curve= 0 ,0
Exp/Cntr(USF)=0,0
Exp/Cntr=0.3,0.1

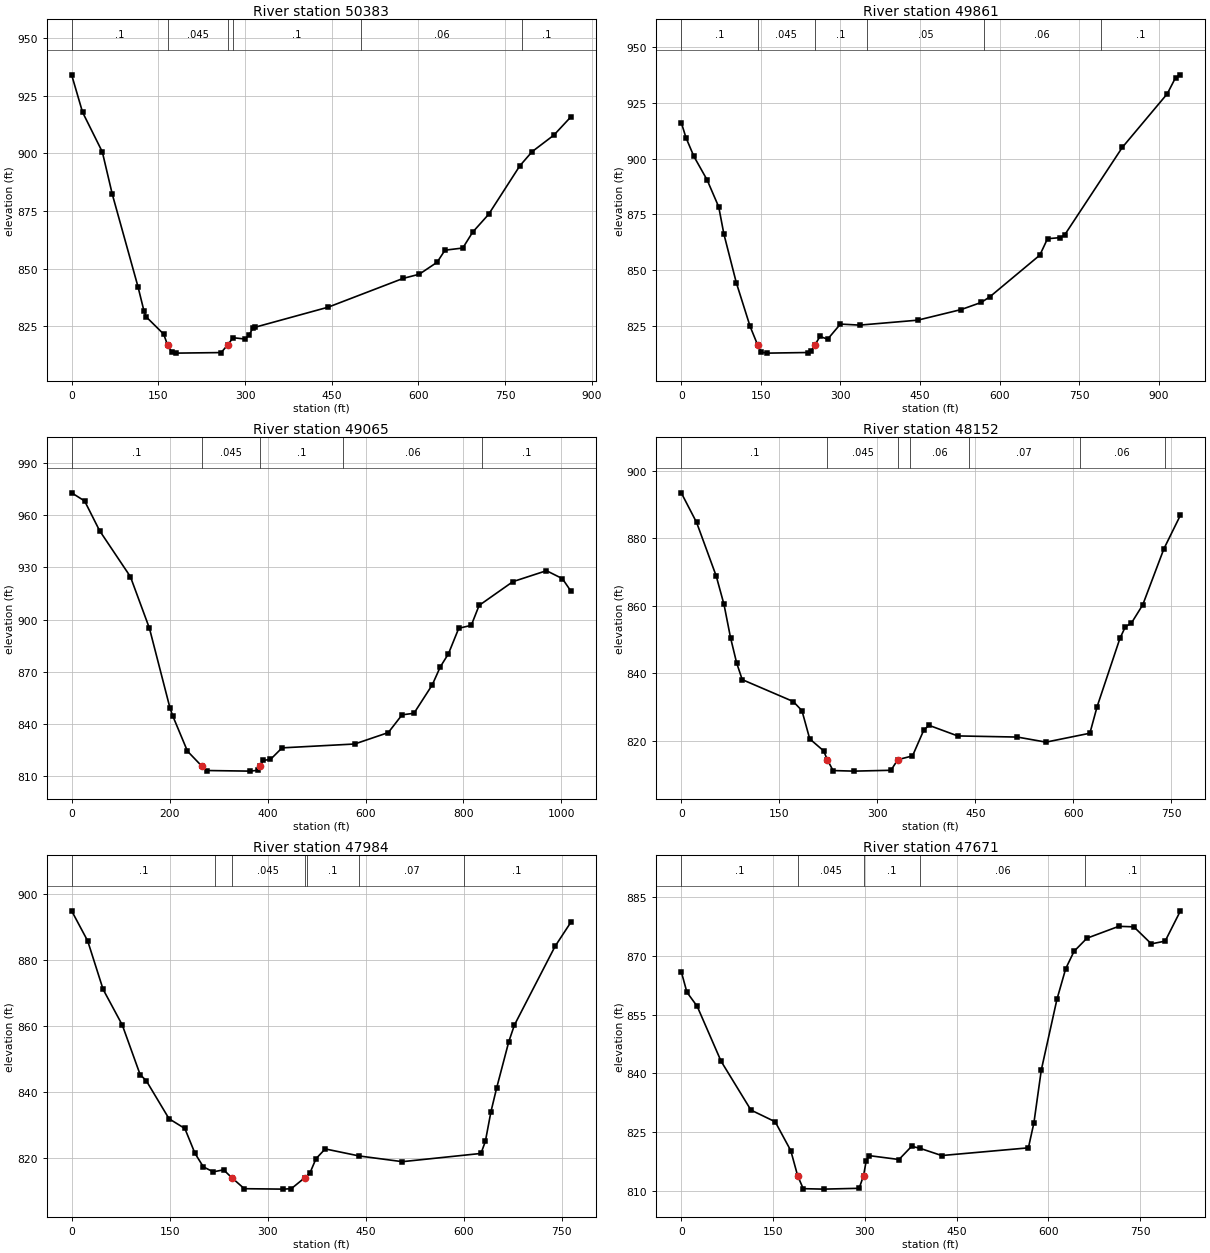
Type RM Length L Ch R = 1 ,50383   ,537.7,521.7,503.2
XS GIS Cut Line= 2
1678505.02485693529388.0789328961678754.01309902530214.994012107
#Sta/Elev= 30
       0  934.12    18.9  917.91    53.1  900.69    70.3  882.37   114.8  842.23
   125.1  831.76   128.5  829.28   159.3  821.64  165.92816.9547     173  813.91
   179.9  813.42   258.7  813.66  269.89816.9571   279.3  820.11   299.8  819.53
   306.7  821.07   313.5   824.3   316.9  824.62   443.7  833.34   573.6  845.84
   601.3  847.63   632.2  852.81   645.9  858.07   676.7     859   693.8  865.89
   721.3  873.58   775.4  894.66   796.6  900.79   834.3  907.97   863.6  915.86
#Mann= 6 ,-1,0
       0      .1       0  165.92    .045       0  269.89     .06       0
     280      .1       0     500     .06       0     780      .1       0
Bank Sta=165.92,269.89
XS Rating Curve= 0 ,0
Exp/Cntr(USF)=0,0
Exp/Cntr=0.3,0.1

Type RM Length L Ch R = 1 ,49861   ,817.9,795.7,772.2
XS GIS Cut Line= 2
1677976.03759084529640.526388451  1678520.320417530407.598557967
#Sta/Elev= 30
       0  916.15     8.9  909.36    23.8  900.99    48.6  890.52    70.6  878.39
    80.3  866.27   103.8  844.42   129.7  824.93  144.16816.4894   150.9  813.39
     162  812.97   239.6  813.25     245  813.88  251.29816.4874   261.5  820.42
   275.8  819.21   299.9  825.97   336.1   825.5   445.4  827.71   527.4  832.46
   565.4  835.67   581.5  838.18   675.6   856.8   690.1  864.15   714.3  864.66
   722.3  865.81   830.9  904.97   915.7  928.99   931.5  936.27   940.6  937.48
#Mann= 6 ,-1,0
       0      .1       0  144.16    .045       0  251.29      .1       0
     350     .05       0     570     .06       0     790      .1       0
Bank Sta=144.16,251.29
XS Rating Curve= 0 ,0
Exp/Cntr(USF)=0,0
Exp/Cntr=0.3,0.1

Type RM Length L Ch R = 1 ,49065   ,907,913.9,913.2
XS GIS Cut Line= 6
1677269.46849158530202.3778849241677350.22850068530250.690124258
1677571.42654909530393.3210725931677637.47136451530430.423032507
1677712.56701484 530480.153904171678116.58359526530767.861334011
#Sta/Elev= 30
       0  972.87    26.5  968.19    57.1   951.1     120  924.63   158.9  894.92
   200.7  849.19   206.5  844.53   236.5  824.26  266.37815.4836   275.8  813.13
   364.5  812.78   379.5  813.23  384.69815.4794   390.8  818.96   405.9  819.49
   429.6  826.16   577.8  828.38   646.5  834.95   674.7  845.18   698.9  846.04
   736.3   862.4   752.8  872.81   769.3  880.26   790.4  894.96   815.9  896.63
     832  908.12   900.9  921.77   969.5  928.08  1001.9  923.52  1019.2   916.4
#Mann= 5 ,-1,0
       0      .1       0  266.37    .045       0  384.69      .1       0
  553.17     .06       0  838.38      .1       0
Bank Sta=266.37,384.69
XS Rating Curve= 0 ,0
Exp/Cntr(USF)=0,0
Exp/Cntr=0.3,0.1

Type RM Length L Ch R = 1 ,48152   ,167.6,167.8,167.6
XS GIS Cut Line= 2
1676759.18444689530930.1701943791677389.97551874531361.243716834
#Sta/Elev= 30
       0  893.39    23.5   884.6    53.5  868.74    65.4  860.32    75.4  850.48
    84.8  842.97    93.3  838.05   171.4  831.56   184.7  828.86   196.6   820.5
   217.9  816.94   223.5814.3433   232.3  811.11   264.2  810.94   320.9  811.19
  331.44 814.345   353.9  815.44   371.4  823.19   379.4  824.49   423.1  821.37
   514.4  821.03   558.2  819.53   625.4  822.17   636.5  830.08   671.4  850.29
   679.7   853.7   688.9  854.79   706.3  860.21   738.7  876.83     764  886.78
#Mann= 7 ,-1,0
       0      .1       0   223.5    .045       0  331.44      .1       0
     350     .06       0     440     .07       0     610     .06       0
     740      .1       0
Bank Sta=223.5,331.44
XS Rating Curve= 0 ,0
Exp/Cntr(USF)=0,0
Exp/Cntr=0.3,0.1

Type RM Length L Ch R = 1 ,47984   ,307,312.5,319.8
XS GIS Cut Line= 2
1676647.46126332531056.7238890451677278.25233516  531487.7974115
#Sta/Elev= 30
       0  894.89    24.6  885.77    48.2  871.11    77.6   860.3   104.8  845.34
   114.3  843.45   149.1  831.96   173.3  829.01   188.8  821.48   201.6   817.4
   216.7  815.89   232.6   816.5   244.9814.1625   264.3  810.79   323.9  810.66
   336.2  810.79  357.09814.1626   364.5  815.43     374  819.87   388.1  822.83
     440   820.7   506.1  818.97   626.5  821.46   633.2  825.12   641.8  834.13
   650.6  841.38     669  855.25   677.6  860.29   739.8  884.11     764  891.42
#Mann= 7 ,-1,0
       0      .1       0     220     .08       0   244.9    .045       0
  357.09     .08       0     360      .1       0     440     .07       0
     600      .1       0
Bank Sta=244.9,357.09
XS Rating Curve= 0 ,0
Exp/Cntr(USF)=0,0
Exp/Cntr=0.3,0.1

Type RM Length L Ch R = 1 ,47671   ,558.6,575.2,595.7
XS GIS Cut Line= 2
1676498.29561721531295.935813105 1677115.9015184531828.938166188
#Sta/Elev= 30
       0  866.02     9.2  860.75      26  857.15    65.1   843.1   113.9  830.63
   153.5  827.64     179  820.26  190.18813.8588   199.3  810.55   232.5  810.43
   290.7  810.64  297.88813.8584   302.3  817.69     307  818.99   355.8     818
   376.5  821.37     390  820.87   425.6  819.01   567.3  820.98   576.3  827.36
   588.4  840.88     614  858.96   628.3  866.77   641.9  871.19   662.9  874.54
     715  877.58   739.6  877.45   768.2   873.1   790.8   873.8   815.8  881.54
#Mann= 5 ,-1,0
       0      .1       0  190.18    .045       0  297.88      .1       0
     390     .06       0     660      .1       0
Bank Sta=190.18,297.88
XS Rating Curve= 0 ,0
Exp/Cntr(USF)=0,0
Exp/Cntr=0.3,0.1