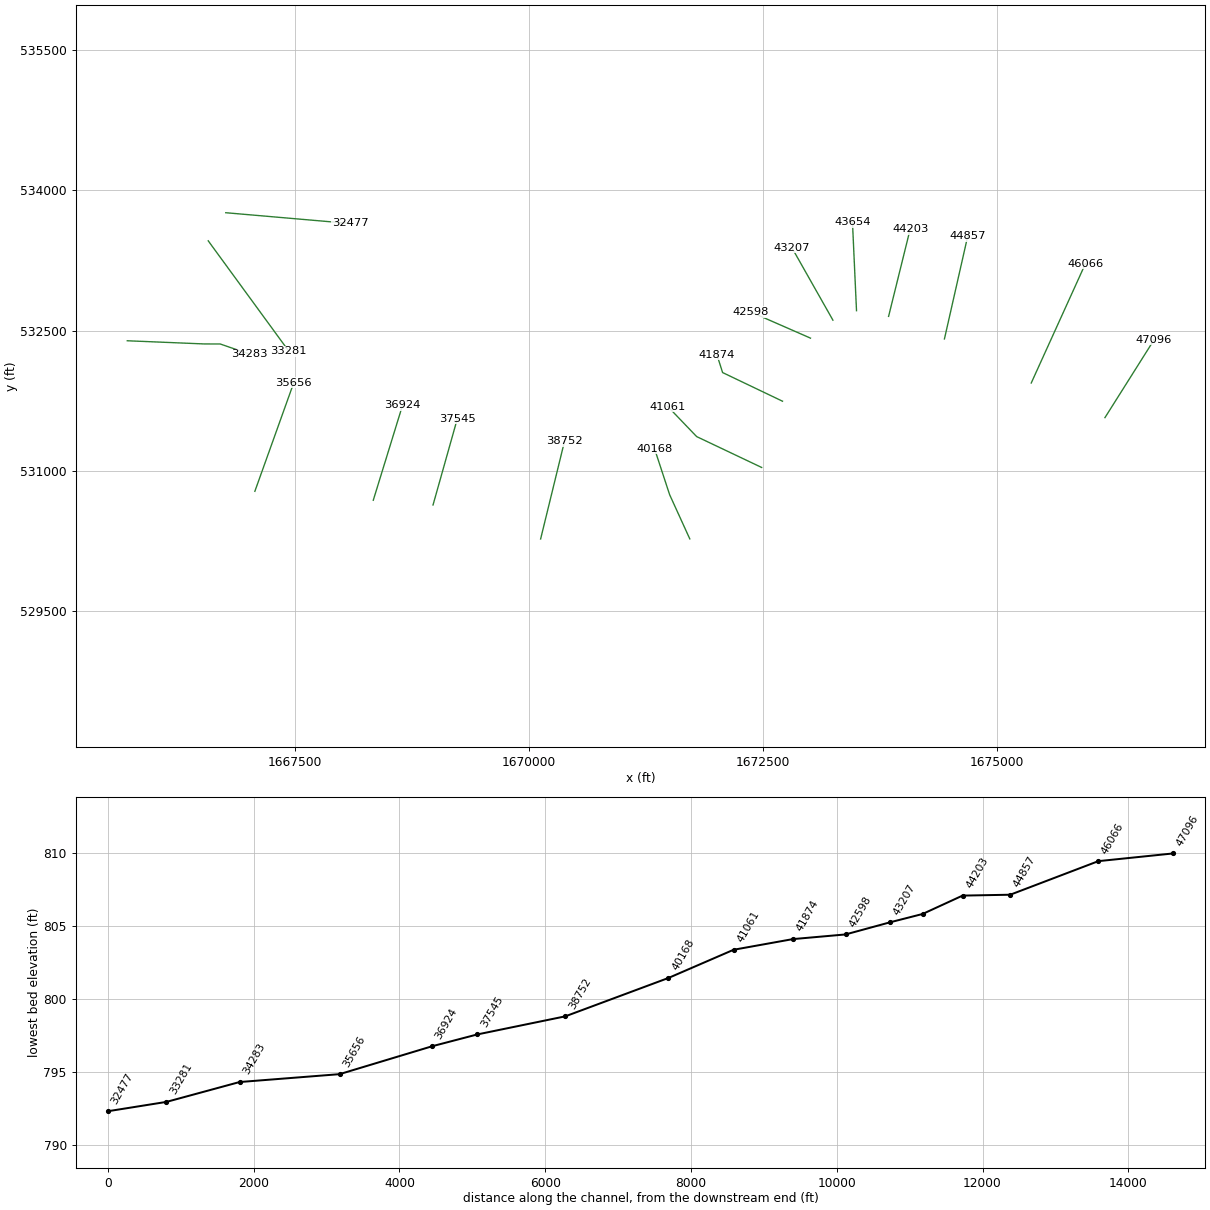
HEC-RAS study WhlingCk.prj: WhlingCk

--- WhlingCk.g01 (geometry) --- (continued)

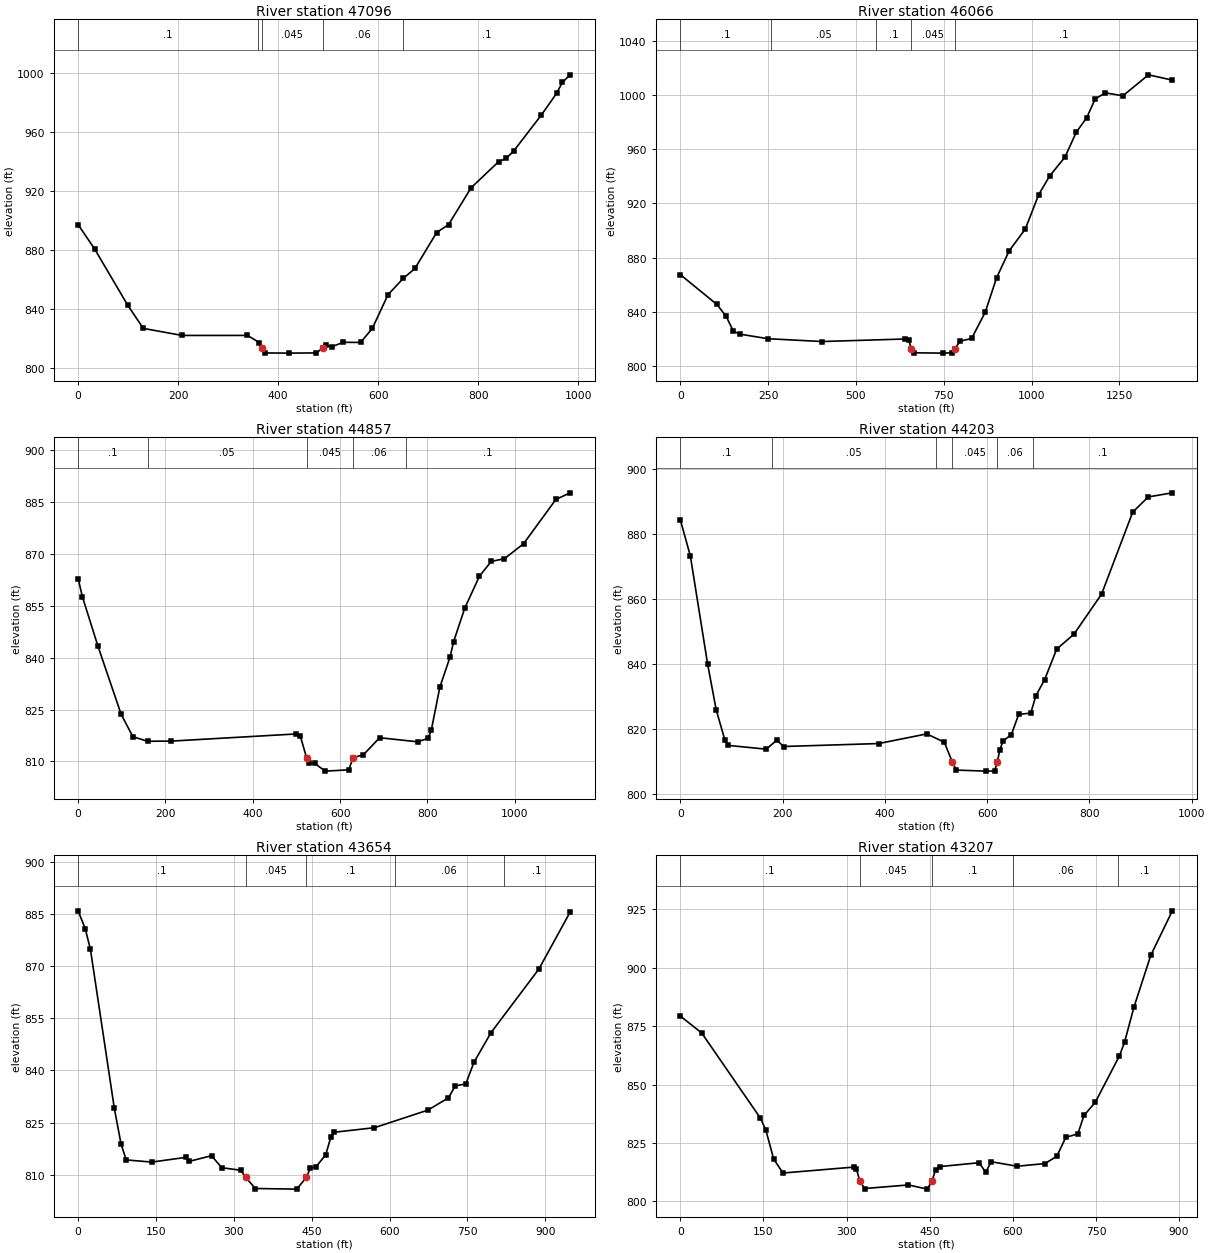
Type RM Length L Ch R = 1 ,47096   ,1003.7,1030.4,1015.5
XS GIS Cut Line= 2
1676151.42106997531569.4872853221676675.96306824532401.422175055
#Sta/Elev= 30
       0  897.21    33.4  880.47    99.3  842.41   130.3  826.78   207.9     822
   338.5  822.01   362.3  817.17  367.84813.4142   373.5  810.12   421.2  809.99
   476.5  810.15  488.74813.4143   494.9  815.42   506.5  814.28   529.8  817.34
   564.7  817.25     588  826.72   619.5  849.69     650  860.74   673.3  867.47
   716.7  891.88   740.5  897.26   785.6  922.27   840.4  939.96   855.6  942.15
   871.1  947.41   926.1   971.7   956.4  986.37   968.1  993.85   983.5  998.96
#Mann= 5 ,-1,0
       0      .1       0     360     .08       0  367.84    .045       0
  488.74     .06       0     650      .1       0
Bank Sta=367.84,488.74
XS Rating Curve= 0 ,0
Exp/Cntr(USF)=0,0
Exp/Cntr=0.3,0.1

Type RM Length L Ch R = 1 ,46066   ,1188.9,1209,1205.4
XS GIS Cut Line= 6
1675363.98444167 531939.181826011675632.76047893 532531.43818742
  1675779.980985532855.8453470021675820.01535375532944.061377928
1675860.69473433533033.7003062521675942.86189283533214.756046504
#Sta/Elev= 30
       0  867.41   104.2  845.39   130.5  836.58     151  825.61   170.1  823.46
   249.4  820.11   403.1  818.03     641  819.91   650.9  818.81  657.62812.4445
   664.7  809.71   749.1  809.46   774.3  809.74  781.56812.4422   795.9  818.23
   829.3  820.28     868  839.67   900.4   865.1   936.4  885.11   982.3  901.16
  1020.1  926.45  1051.7  940.41    1095  954.21  1127.4  972.71    1157  983.32
  1181.2  997.29  1210.3 1001.71  1260.2  999.57  1332.8 1015.05  1400.8 1011.14
#Mann= 5 ,-1,0
       0      .1       0  258.83     .05       0  557.89      .1       0
  657.62    .045       0  781.56      .1       0
Bank Sta=657.62,781.56
XS Rating Curve= 0 ,0
Exp/Cntr(USF)=0,0
Exp/Cntr=0.3,0.1

Type RM Length L Ch R = 1 ,44857   ,644.2,654.1,639.5
XS GIS Cut Line= 2
1674437.07117346 532410.44655352 1674685.8056049533509.446643447
#Sta/Elev= 30
       0  862.92     9.7  857.68    45.3  843.36    98.5  823.61   125.4  817.12
     159  815.81   212.8  815.85   498.8  817.92   508.9  817.29  523.18811.0566
     529  809.37   541.8  809.38     566  807.16   619.9  807.53  629.55811.0554
   653.5  811.91   690.5  816.83   777.7  815.65   801.5  816.67   808.8  818.97
   828.4  831.44   851.8  840.19     860  844.65   885.6  854.38   919.2  863.61
   946.1  867.87   976.4  868.67  1020.2     873  1094.2  885.82  1126.8  887.74
#Mann= 5 ,-1,0
       0      .1       0     160     .05       0  523.18    .045       0
  629.55     .06       0     750      .1       0
Bank Sta=523.18,629.55
XS Rating Curve= 0 ,0
Exp/Cntr(USF)=0,0
Exp/Cntr=0.3,0.1

Type RM Length L Ch R = 1 ,44203   ,533,548.9,550.1
XS GIS Cut Line= 2
 1673840.6161593532651.5666656281674071.58384564533585.589836745
#Sta/Elev= 30
       0  884.43    19.5  873.37    53.3  840.06    70.2  825.87    87.1  816.69
    93.9  815.02   168.2  813.85   188.5  816.65     202  814.68   387.9  815.59
   481.9  818.56   516.3  815.99  531.65809.9696     540  807.42   597.5   807.1
   614.4  807.13   620.2809.9719   624.5  813.51   631.3  816.43   647.2  818.29
   661.7  824.55   685.3  824.97   695.5  830.37   712.4  835.24     736  844.66
   769.8  849.26   823.9  861.61   884.7  886.82   915.1  891.51   962.2  892.77
#Mann= 6 ,-1,0
       0      .1       0     180     .05       0     500      .1       0
  531.65    .045       0   620.2     .06       0     690      .1       0
Bank Sta=531.65,620.2
XS Rating Curve= 0 ,0
Exp/Cntr(USF)=0,0
Exp/Cntr=0.3,0.1

Type RM Length L Ch R = 1 ,43654   ,422.4,446.7,481.3
XS GIS Cut Line= 2
1673497.97178946532712.4812202661673454.82397993533659.194923599
#Sta/Elev= 30
       0  885.89    13.8  880.67    23.7  874.78    69.7  829.08    82.8  818.71
    92.7  814.24   141.9  813.62   207.6  814.98   214.2  813.83   256.9  815.46
   276.6     812   313.2  811.27  322.73809.1896   341.5  806.02   421.1  805.84
  439.65809.1921   447.4  811.95   457.7  812.18   476.9  815.72   486.8  820.78
   493.3   822.2   570.8  823.51     674  828.58   713.4  832.11   726.5  835.55
   746.7  836.09   762.6  842.37   795.5  850.88   887.4  869.11   947.7  885.51
#Mann= 5 ,-1,0
       0      .1       0  322.73    .045       0  439.65      .1       0
     610     .06       0     820      .1       0
Bank Sta=322.73,439.65
XS Rating Curve= 0 ,0
Exp/Cntr(USF)=0,0
Exp/Cntr=0.3,0.1

Type RM Length L Ch R = 1 ,43207   ,579.7,609.4,643.1
XS GIS Cut Line= 2
1673246.15778887 532610.804676151672809.03945698533383.517082206
#Sta/Elev= 30
       0  879.31    38.5  872.09     144   835.8     154  830.74   168.4  818.13
   185.3  812.16   313.6  814.71   317.7  813.89  323.69808.8348   332.5  805.53
   411.6  807.06   445.6  805.27  454.16808.8336   460.6   813.6   468.2  814.92
   539.2  816.57   551.1  812.44   560.8     817   607.6  815.06     658  816.21
   679.3  819.33   695.6  827.42   717.3  828.91   728.3  836.78   748.6  842.36
   792.3  862.26   801.6  868.16   818.4  883.02   848.9  905.32   887.8  924.35
#Mann= 5 ,-1,0
       0      .1       0  323.69    .045       0  454.16      .1       0
     600     .06       0     790      .1       0
Bank Sta=323.69,454.16
XS Rating Curve= 0 ,0
Exp/Cntr(USF)=0,0
Exp/Cntr=0.3,0.1

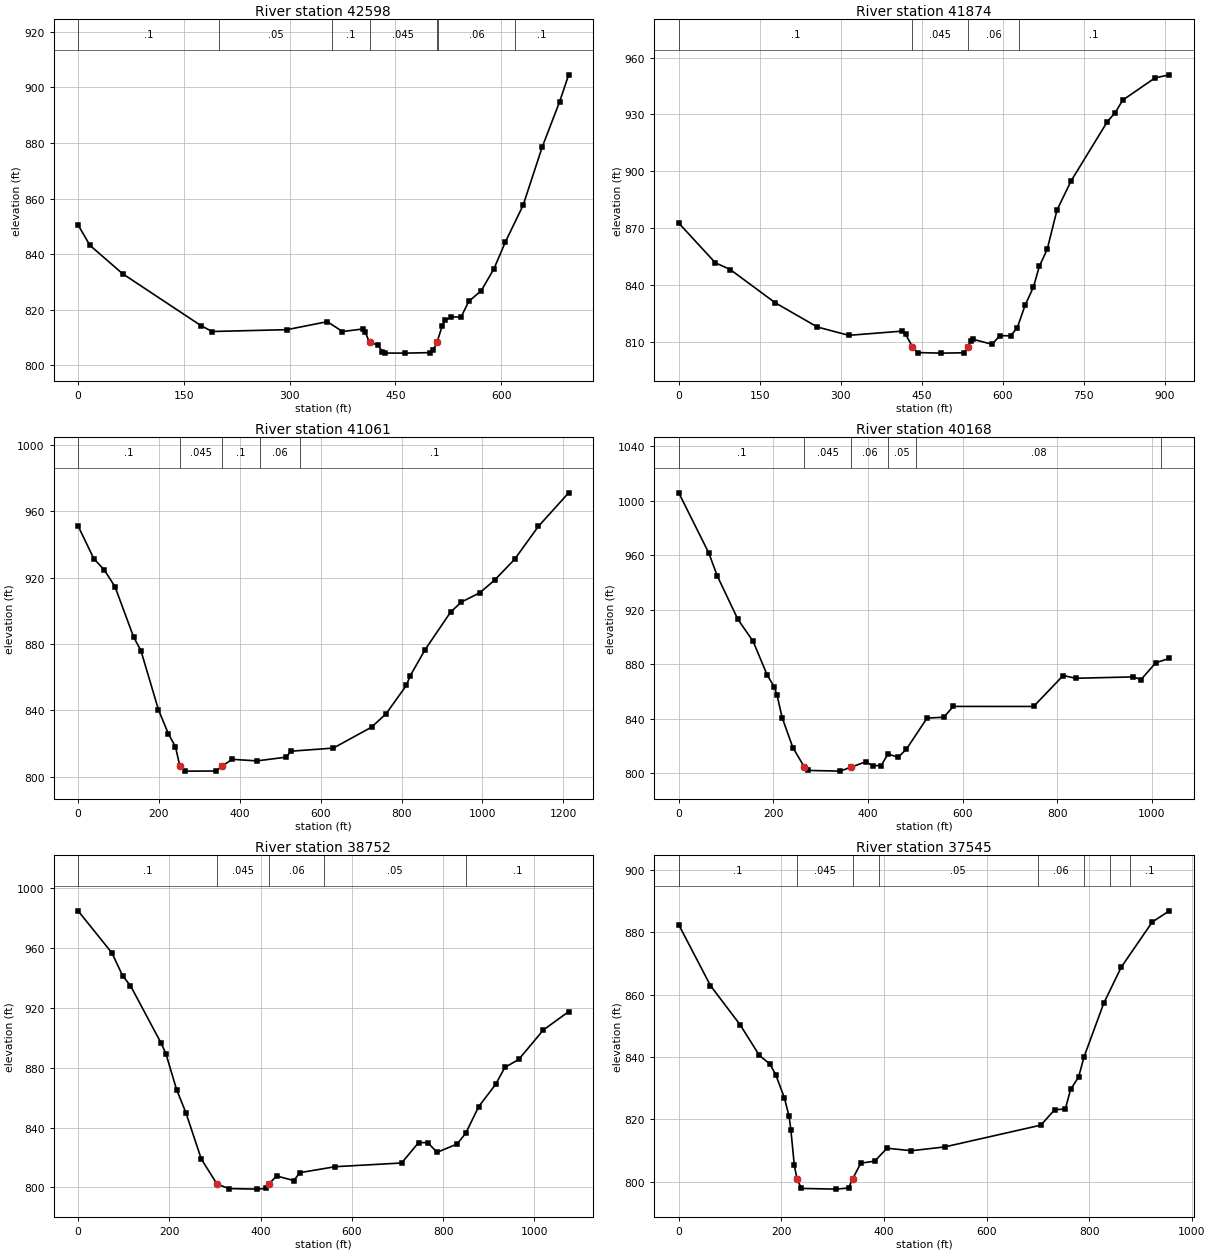
Type RM Length L Ch R = 1 ,42598   ,724.1,723.2,720.6
XS GIS Cut Line= 2
 1673006.4477359532419.0366337711672369.10100681532698.228342528
#Sta/Elev= 30
       0  850.52    16.8  843.18    63.3  832.95   174.4  814.31   190.1  812.21
   296.2  812.87   353.5  815.75     375   812.2   403.6  813.11   407.2     812
  413.48 808.269   425.1  807.38   431.7   804.9   435.8  804.47   463.3  804.44
     499  804.62     504  805.64  508.97808.2694   516.4  814.17   520.5  816.17
     529  817.44   543.3  817.42     554  823.01     572  826.93   589.9   834.8
   606.1  844.41   631.2  857.58   658.4  878.58     683   894.8   695.8  904.46
#Mann= 7 ,-1,0
       0      .1       0     200     .05       0     360      .1       0
  413.48    .045       0  508.97      .1       0     510     .06       0
     620      .1       0
Bank Sta=413.48,508.97
XS Rating Curve= 0 ,0
Exp/Cntr(USF)=0,0
Exp/Cntr=0.3,0.1

Type RM Length L Ch R = 1 ,41874   ,812.4,812.9,808.6
XS GIS Cut Line= 3
1672707.67249918531744.9344259011672067.89291673532051.061397605
  1672007.357574532241.040482292
#Sta/Elev= 30
       0  872.69    67.7  851.77    95.3  848.21   178.9  830.63   256.8  817.88
     315   813.5   413.2  815.72     420   814.1  432.79807.4693   442.3  804.41
     486  804.12   528.3   804.3  536.34807.4725   540.5  810.71   544.2  811.48
   579.9   808.8   595.1  813.35   614.4  813.23   626.7  817.35   641.4  829.32
   656.9     839   667.8  849.89   682.4  858.92   700.5  879.58   726.6  894.94
   793.9  926.26   808.5  931.01   822.2  937.56   882.1  949.28   908.6   950.9
#Mann= 4 ,-1,0
       0      .1       0  432.79    .045       0  536.34     .06       0
     630      .1       0
Bank Sta=432.79,536.34
XS Rating Curve= 0 ,0
Exp/Cntr(USF)=0,0
Exp/Cntr=0.3,0.1

Type RM Length L Ch R = 1 ,41061   ,919.7,893.2,847.4
XS GIS Cut Line= 3
 1672485.1965023531036.7713935871671790.63270698531366.787900504
1671483.21929132 531687.69489272
#Sta/Elev= 30
       0  951.26    39.2  931.41    64.7  924.83    91.6  914.45   137.3  884.33
   155.5  876.03   198.9  840.34   223.5  825.82   240.8  818.12  251.82806.3781
   264.4  803.39   340.7  803.46  356.97806.3826   380.7  810.52   442.4  809.56
   515.1  811.83     526   815.4   631.3  817.28   725.8  829.89   762.1  838.06
   811.9  855.04   821.6  860.92   858.3  876.64   921.2  899.22   947.9  905.34
   993.4  910.91    1030  918.52  1079.7  931.15  1138.7  951.05  1213.4  971.23
#Mann= 5 ,-1,0
       0      .1       0  251.82    .045       0  356.97      .1       0
     450     .06       0     550      .1       0
Bank Sta=251.82,356.97
XS Rating Curve= 0 ,0
Exp/Cntr(USF)=0,0
Exp/Cntr=0.3,0.1

Type RM Length L Ch R = 1 ,40168   ,1440.2,1415.9,1370.7
XS GIS Cut Line= 6
1671717.42414951530273.5650785121671642.23926051 530438.48600851
1671569.64721408530597.7196139251671538.53605583530665.962587669
1671502.24019668530745.5795544241671340.77181705531237.786487999
#Sta/Elev= 30
       0 1005.77    63.5  961.52    81.5  944.66   124.8  912.96   157.2   896.7
   186.7  872.13   201.6  863.36   207.7  857.19   218.5  840.71   241.2  818.66
  265.52804.4412   272.6  801.98   341.1  801.46  364.58804.4406   395.2  808.33
   409.6  805.47   427.6  805.54   442.1  814.01   463.7  811.67   480.8  817.44
   524.7   840.4   560.2  841.03     580  848.96     750  848.94   812.4  871.65
   838.9  869.63   960.6  870.64   977.1  868.71  1008.1  881.05  1036.8  884.21
#Mann= 6 ,-1,0
       0      .1       0  265.52    .045       0  364.58     .06       0
  441.25     .05       0  501.25     .08       0 1018.75     .07       0
Bank Sta=265.52,364.58
XS Rating Curve= 0 ,0
Exp/Cntr(USF)=0,0
Exp/Cntr=0.3,0.1

Type RM Length L Ch R = 1 ,38752   ,1203.1,1207.7,1196.2
XS GIS Cut Line= 2
1670124.29203981530272.4190747191670379.61138938 531316.90732297
#Sta/Elev= 30
       0   984.9    74.1  956.78    97.8  941.39   114.7  934.93   182.2  896.33
   192.4  889.45     216  865.32   236.3  849.94     270  818.99  304.58802.1768
   330.8   799.2   391.6  798.83   411.9  799.28  417.53802.1735   435.5  807.61
   472.7  804.56   486.2  809.85   563.8  813.84   709.1   816.3   746.3  829.94
   766.5   829.9   786.8  823.44   830.7  828.97     850  836.41     878  854.01
   915.1  868.84   935.4  880.22   965.8  885.54  1019.8  905.25  1075.2   917.5
#Mann= 5 ,-1,0
       0      .1       0  304.58    .045       0  417.53     .06       0
     540     .05       0     850      .1       0
Bank Sta=304.58,417.53
XS Rating Curve= 0 ,0
Exp/Cntr(USF)=0,0
Exp/Cntr=0.3,0.1

Type RM Length L Ch R = 1 ,37545   ,619.8,620.3,617.2
XS GIS Cut Line= 2
1668975.35496673 530636.05572411 1669234.5427913531556.752772569
#Sta/Elev= 30
       0  882.45    61.7  862.95   119.7  850.33   157.2  840.52   177.6  837.76
   189.2  834.28   205.9  826.89   215.1  820.92   218.5  816.71   225.3  805.18
  230.48800.9481     239  797.82   307.1  797.59     331  797.95  339.19800.9502
   354.9  805.92   382.1  806.58     406  810.72   453.7  809.92   518.5  811.14
   705.9  818.13   733.2  823.13   753.6  823.26   763.9  829.59   779.6  833.59
   790.2  840.08   828.6  857.26   862.7  868.85   923.2  883.35   956.5  886.93
#Mann= 8 ,-1,0
       0      .1       0  230.48    .045       0  339.19     .06       0
     390     .05       0     700     .06       0     790      .1       0
     840     .05       0     880      .1       0
Bank Sta=230.48,339.19
XS Rating Curve= 0 ,0
Exp/Cntr(USF)=0,0
Exp/Cntr=0.3,0.1

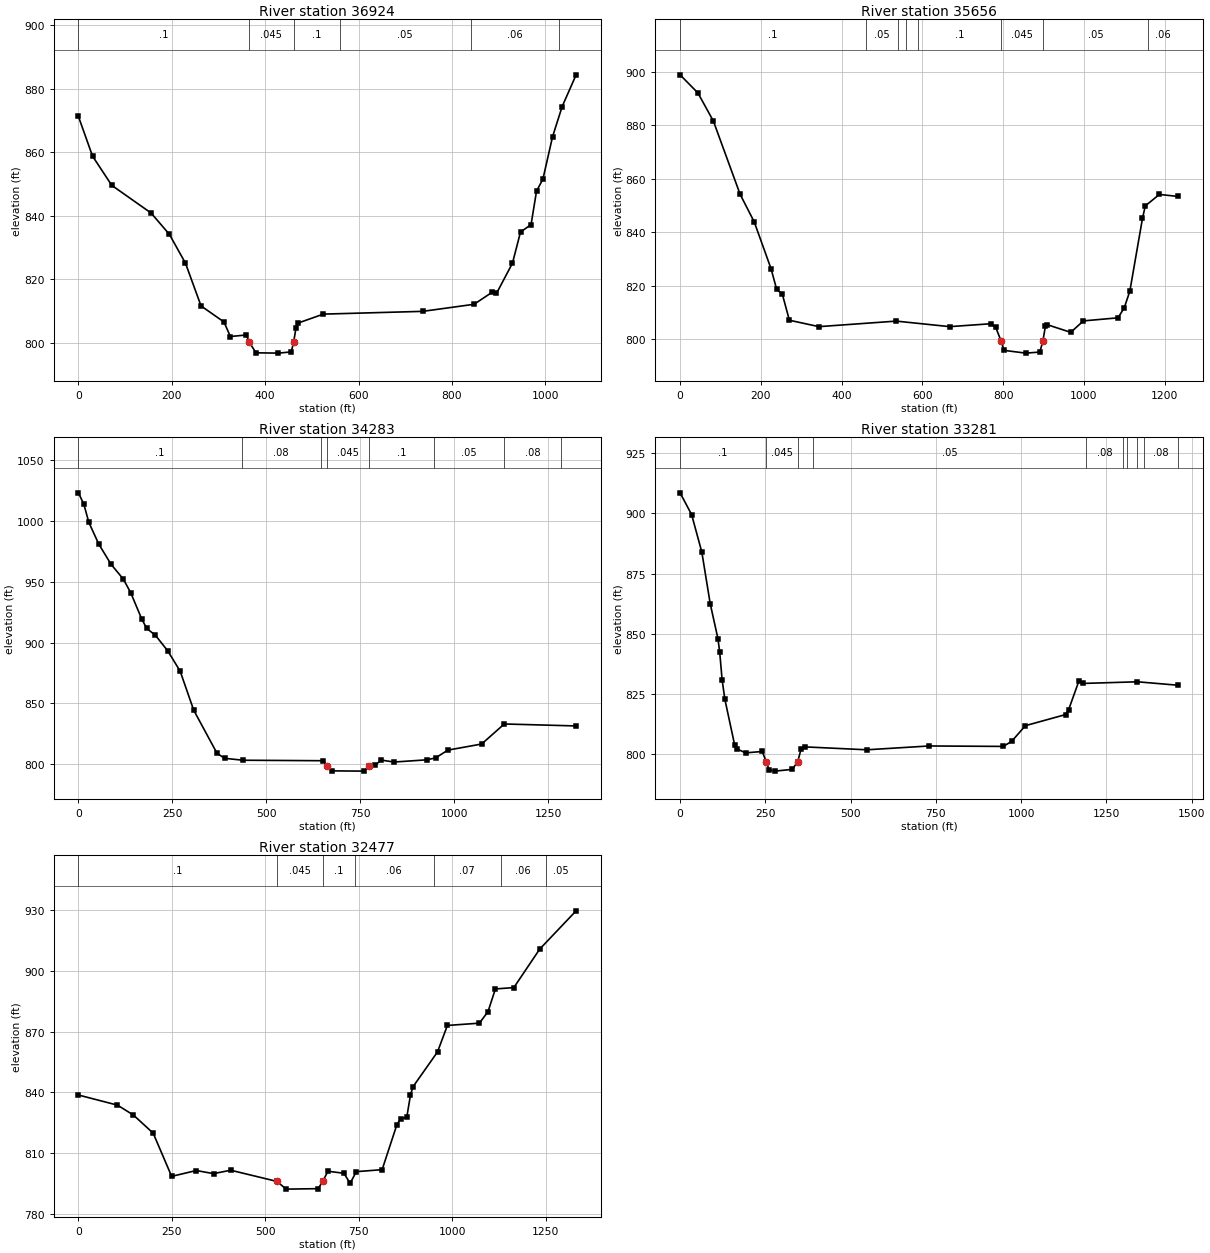
Type RM Length L Ch R = 1 ,36924   ,1260.1,1268.6,1264
XS GIS Cut Line= 2
 1668337.0565928530686.3458990261668650.83289783531705.044313987
#Sta/Elev= 30
       0  871.22    30.2  858.75    71.4  849.56   155.8  840.83   194.9  834.12
   229.3  825.06   262.6  811.63   311.7  806.58   325.4  802.01   359.7  802.49
  365.52800.3018   380.3  796.88   428.4  796.78   455.8  797.17  460.97800.3004
   466.1  804.84   469.6   806.2   524.5  809.05   737.3  809.92   847.2  812.14
   885.4  815.86   895.3  815.54   929.6  825.09   946.8  834.88   969.4   837.2
   981.1  847.74   994.8  851.52  1015.4  864.84    1036  874.34  1065.9  884.32
#Mann= 6 ,-1,0
       0      .1       0  365.52    .045       0  460.97      .1       0
     560     .05       0     840     .06       0    1030      .1       0
Bank Sta=365.52,460.97
XS Rating Curve= 0 ,0
Exp/Cntr(USF)=0,0
Exp/Cntr=0.3,0.1

Type RM Length L Ch R = 1 ,35656   ,1397.1,1372.5,1257.4
XS GIS Cut Line= 2
1667072.39958257530781.8638001011667487.90245225531942.406298157
#Sta/Elev= 30
       0  898.91    44.2  892.13    82.5  881.62   148.7  854.25   183.6  843.96
   225.4  826.39   239.3  818.66   253.2  816.96   270.7  807.17   343.9  804.77
   535.5  806.84   667.9  804.77     769  805.85   781.9  804.47  795.51799.2549
   802.4   795.9   856.3  794.87     891  795.27  898.45799.2559   904.9  804.92
   908.4  805.55   967.6  802.64     999  806.92  1084.7  808.07  1100.1  811.79
    1114  818.04  1145.3  845.24  1152.3  849.92  1187.2   854.2  1232.7  853.45
#Mann= 8 ,-1,0
       0      .1       0     460     .05       0     540      .1       0
     560     .05       0     590      .1       0  795.51    .045       0
  898.45     .05       0    1160     .06       0
Bank Sta=795.51,898.45
XS Rating Curve= 0 ,0
Exp/Cntr(USF)=0,0
Exp/Cntr=0.3,0.1

Type RM Length L Ch R = 1 ,34283   ,1039.1,1002.4,951.5
XS GIS Cut Line= 6
1665709.66057451532390.8452927621666359.49785751532364.016934335
1666459.41268392532359.8922706691666534.34888576532356.798444837
1666701.85166821532356.6708275821667014.86428859532248.354884503
#Sta/Elev= 30
       0 1022.96    14.5 1013.53    27.6  998.75    54.1  980.87    86.7  964.29
   119.5  952.05   139.2  940.84   168.8  919.02   181.9  911.52   204.9  905.91
   237.7   893.1   270.6  876.48   306.7   844.4   368.7     809   388.8  804.87
     438  803.28   651.5  802.88  662.64 798.139   674.5  794.54   759.8  794.33
  772.77798.1398   789.4  799.28   805.8   803.4   839.8   801.8   927.2  803.63
   950.2  805.21     983   811.6  1072.7  816.59    1133  833.07  1324.1  831.45
#Mann= 8 ,-1,0
       0      .1       0  434.14     .08       0  645.39      .1       0
  662.64    .045       0  772.77      .1       0  945.39     .05       0
 1132.89     .08       0 1282.89      .1       0
Bank Sta=662.64,772.77
XS Rating Curve= 0 ,0
Exp/Cntr(USF)=0,0
Exp/Cntr=0.3,0.1

Type RM Length L Ch R = 1 ,33281   ,742.2,804,837.9
XS GIS Cut Line= 2
1666574.26224921533459.0365099671667434.48213861 532280.22621333
#Sta/Elev= 30
       0  908.52    33.9  899.47    63.9  883.83    88.3  862.54     111  847.99
   116.2  842.41   123.2  830.95   131.3  822.82   159.8  803.98   167.9   802.1
   192.3  800.56     241  801.12  252.49796.9429   261.1  793.45   277.6  792.97
   329.2   793.7  345.05796.9437     355  802.24   366.8  803.03   547.6  801.83
   730.7  803.42   947.7  803.23   972.1   805.3  1012.5  811.84  1130.5  816.46
  1139.3  818.48  1169.8  830.52  1181.5  829.38  1341.2  830.06  1459.3  828.64
#Mann= 10 ,-1,0
       0      .1       0  252.49    .045       0  345.05      .1       0
     390     .05       0    1190     .08       0    1300      .1       0
    1310     .08       0    1340      .1       0    1360     .08       0
 1459.31     .05       0
Bank Sta=252.49,345.05
XS Rating Curve= 0 ,0
Exp/Cntr(USF)=0,0
Exp/Cntr=0.3,0.1

Type RM Length L Ch R = 1 ,32477   ,1141.5,1199,1245
XS GIS Cut Line= 2
1666761.68628181533759.3119873451668088.18635709533644.418280037
#Sta/Elev= 30
       0  838.73   104.5  833.74   147.3  828.82     200  819.92   249.4  798.62
   315.3   801.5   361.4  799.97   407.5  801.65  531.34796.1195   555.7  792.33
   641.3  792.56   653.4   796.1   667.6  801.16   710.5  800.13   726.9  795.17
   743.4  800.95   812.5  801.92   852.1  824.16   861.9  826.96   878.4   827.7
   888.3  838.67   894.9  842.75   960.7  859.98   987.1  873.03  1072.7  874.15
  1095.8  879.84  1115.5  891.03  1164.9   891.7  1234.1  910.67  1331.5  929.54
#Mann= 7 ,-1,0
       0      .1       0  531.34    .045       0   653.4      .1       0
     740     .06       0     950     .07       0    1130     .06       0
    1250     .05       0
Bank Sta=531.34,653.4
XS Rating Curve= 0 ,0
Exp/Cntr(USF)=0,0
Exp/Cntr=0.3,0.1