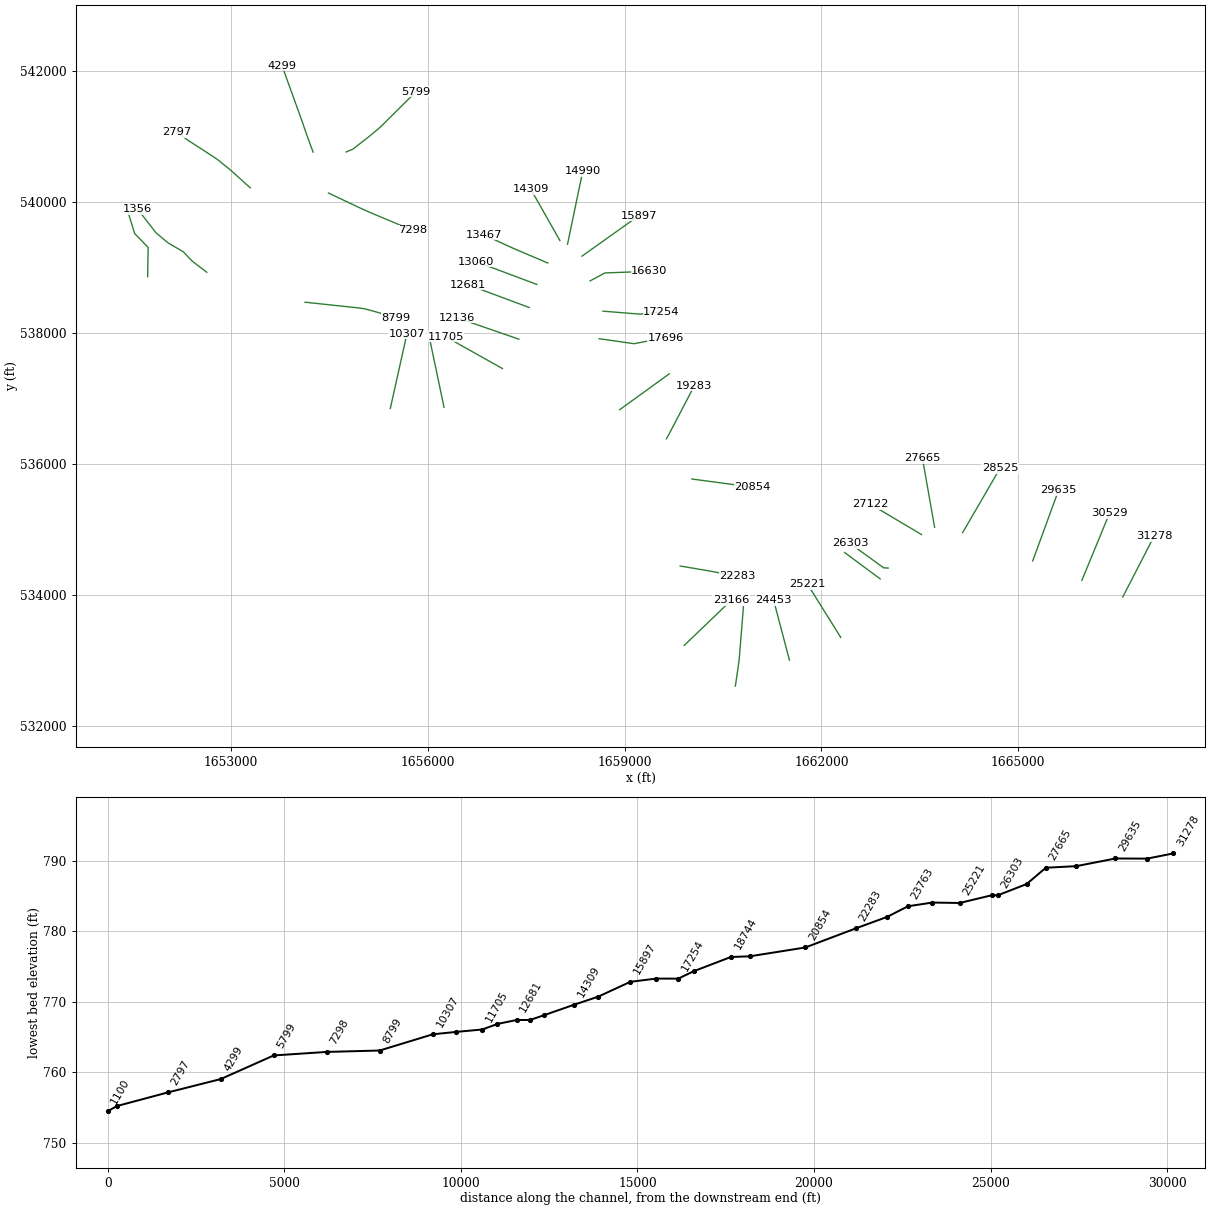
HEC-RAS study WhlingCk.prj: WhlingCk

--- WhlingCk.g01 (geometry) --- (continued)

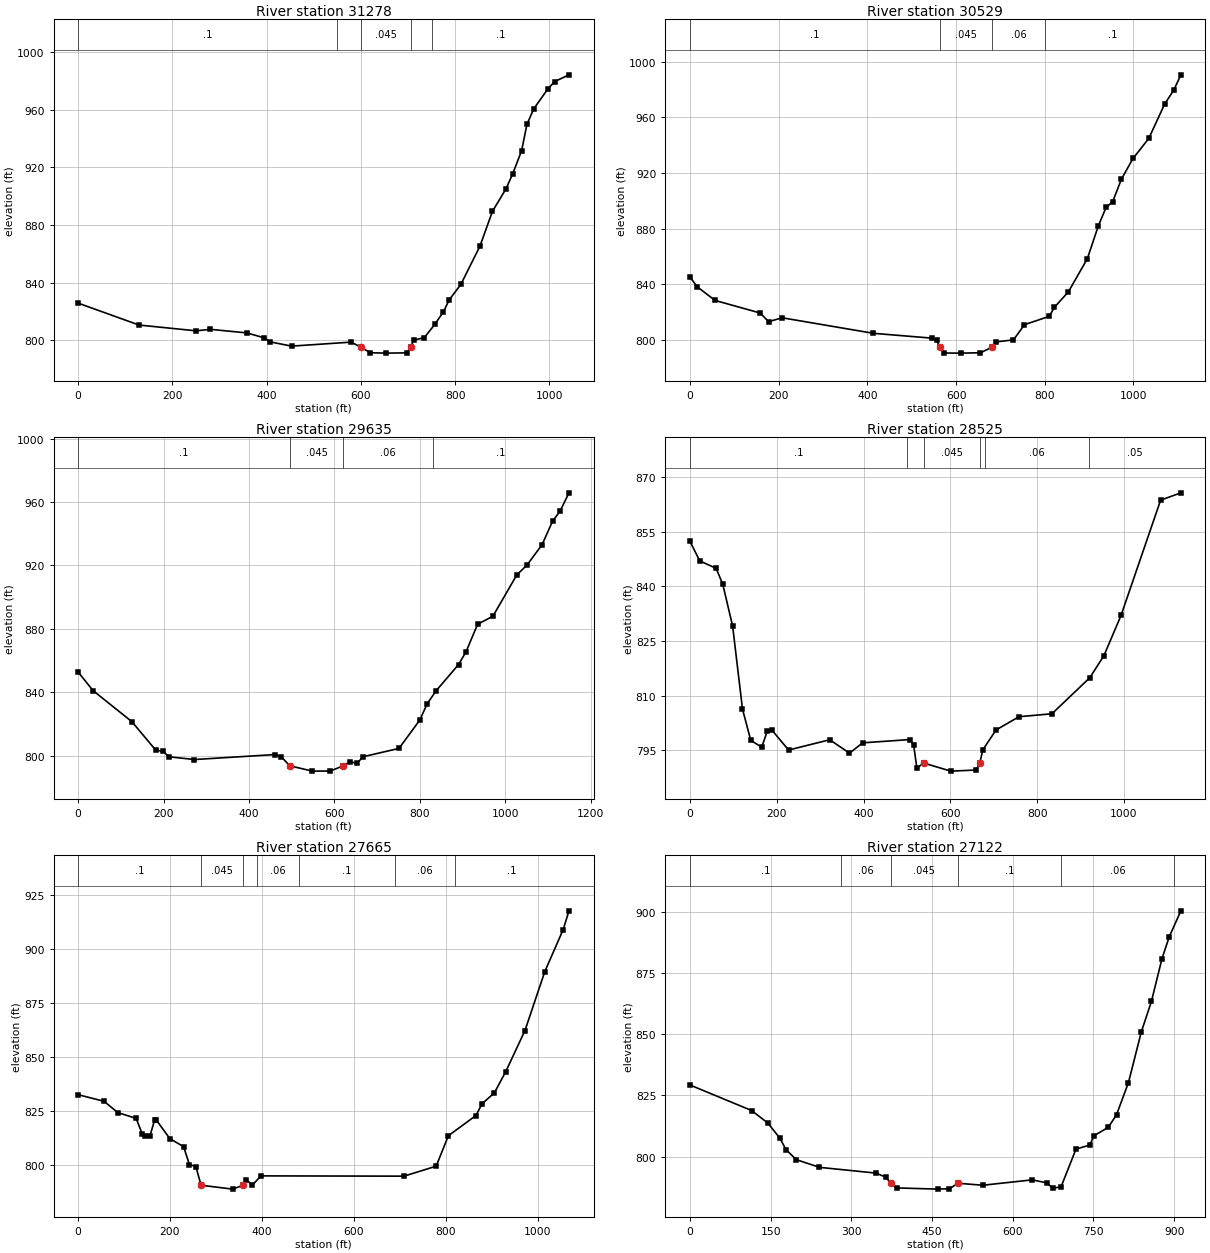
Type RM Length L Ch R = 1 ,31278   ,734.5,748.9,742.3
XS GIS Cut Line= 2
1666593.78479591533969.4734677751667070.76776261534895.586381224
#Sta/Elev= 30
       0  825.75   129.5  810.52   250.2  806.52   280.8  807.54   358.1  805.07
   395.2  801.63   406.8  798.89   453.1  795.89   579.8  798.68  599.98795.1059
   620.3   791.3   653.5  791.03   697.8  791.22  705.43795.1014   712.5  800.04
   734.7  801.79   756.8  810.93   775.3  819.76   787.6  828.05   812.2  838.71
   852.8  865.32   879.3  889.48   908.1  905.13     922  915.32   941.3  931.68
   952.4  949.78     967  960.68   996.7  974.37  1011.5   979.6  1041.7  984.25
#Mann= 5 ,-1,0
       0      .1       0     550     .06       0  599.98    .045       0
  705.43     .06       0     750      .1       0
Bank Sta=599.98,705.43
XS Rating Curve= 0 ,0
Exp/Cntr(USF)=0,0
Exp/Cntr=0.3,0.1

Type RM Length L Ch R = 1 ,30529   ,853.6,894.1,871.9
XS GIS Cut Line= 2
1665970.57347445 534223.632274851666391.85040124535247.230758135
#Sta/Elev= 30
       0  845.07    16.3  838.06    56.5  828.23   158.3  819.17   177.2  812.93
   207.9  815.73   413.7  804.55     545  801.09   556.7  799.49  562.89794.6176
   573.4  790.37     611  790.29     655  790.56  681.51794.6202   690.4  798.37
   729.5  799.84   754.3  810.78   810.5  816.81   821.7  823.27   853.3  834.43
     896  858.27     921  882.11   938.5  895.35     953  899.19     973  915.64
     999  930.42  1034.6  944.86  1070.1  969.46  1091.3  979.86  1106.9  990.63
#Mann= 4 ,-1,0
       0      .1       0  562.89    .045       0  681.51     .06       0
     800      .1       0
Bank Sta=562.89,681.51
XS Rating Curve= 0 ,0
Exp/Cntr(USF)=0,0
Exp/Cntr=0.3,0.1

Type RM Length L Ch R = 1 ,29635   ,1109.7,1110.2,1088.2
XS GIS Cut Line= 2
1665220.08932571534517.6363743571665614.67377505 535596.94089755
#Sta/Elev= 30
       0  852.86    34.9  841.12   125.7  821.56   181.6  803.62   199.1  802.75
   213.1  799.35   272.5  797.62   461.1  800.76   475.1  799.52  495.35793.7014
   548.4  790.31   590.3  790.38  621.14793.7018   635.7  796.12   653.2  795.34
   667.2  799.39   751.3  804.64   799.9   822.5   817.4  832.88   838.3  841.02
   890.7  857.52   908.2  865.56   935.3  882.93   971.1     888    1027  914.02
  1051.4  920.41  1086.4   933.2  1110.8  947.95  1128.3  954.23  1149.2  965.81
#Mann= 4 ,-1,0
       0      .1       0  495.35    .045       0  621.14     .06       0
     830      .1       0
Bank Sta=495.35,621.14
XS Rating Curve= 0 ,0
Exp/Cntr(USF)=0,0
Exp/Cntr=0.3,0.1

Type RM Length L Ch R = 1 ,28525   ,796.2,860,888.1
XS GIS Cut Line= 2
1664152.76131578534951.0077027351664720.55141765535929.398012089
#Sta/Elev= 30
       0  852.43    22.4  847.04    60.3  844.98    75.5  840.63    98.3   829.1
     121  806.29     140   797.7   165.3  795.79   177.9  800.16   189.3  800.44
   227.2  795.02   322.1  797.85   367.6  794.16   397.9     797   507.9  797.91
   515.5  796.29   522.9  790.03   538.3  791.45     601  789.22   659.4  789.52
  667.79  791.42   674.8  795.08   705.3  800.54   758.3  804.19   834.1  804.99
   921.4  814.91     954     821   993.4  832.06  1084.5  863.73  1131.2  865.75
#Mann= 6 ,-1,0
       0      .1       0     500     .06       0   538.3    .045       0
  667.79     .07       0     680     .06       0     920     .05       0
Bank Sta=538.3,667.79
XS Rating Curve= 0 ,0
Exp/Cntr(USF)=0,0
Exp/Cntr=0.3,0.1

Type RM Length L Ch R = 1 ,27665   ,512.1,542.4,606.4
XS GIS Cut Line= 2
1663724.92374071535032.9172434941663539.23694102536085.142441732
#Sta/Elev= 30
       0  832.71    56.4  829.65    86.4  824.44   126.4  821.72   139.7  814.52
   146.4   813.5   156.4  813.56   166.4   820.9   169.7  821.15   199.7  812.37
   229.7  808.65   242.3  800.38   256.3  799.42  267.72790.8126   336.3     789
  359.67 790.811   366.3  793.21   379.6  790.94   398.1  795.13   709.4     795
   779.4  799.62     806  813.72     866  823.07   879.3  828.53     906  833.51
   930.5  843.22   972.6  862.34  1015.9  889.68  1055.9  909.14  1068.5  917.79
#Mann= 7 ,-1,0
       0      .1       0  267.72    .045       0  359.67     .07       0
     390     .06       0     480      .1       0     690     .06       0
     820      .1       0
Bank Sta=267.72,359.67
XS Rating Curve= 0 ,0
Exp/Cntr(USF)=0,0
Exp/Cntr=0.3,0.1

Type RM Length L Ch R = 1 ,27122   ,822.9,819.2,786.4
XS GIS Cut Line= 2
 1663524.9598424534921.6860086621662740.76474501535388.234911471
#Sta/Elev= 30
       0  829.25   114.5  818.82   144.9  813.67   166.8   807.6   178.6  802.84
   197.5  798.75   240.6   795.6   345.9  793.24   364.7  791.49  372.83789.0845
     384  787.19   460.7  786.69   482.4  786.85   498.1  789.09   544.4  788.28
   636.3  790.48   663.1  789.25   674.5  787.06   689.8  787.64   717.6  803.07
   743.2  804.68   750.9  808.48   777.6  811.96   792.9  817.09   815.1  830.27
     839  850.99   857.8  863.42   877.3  880.82   890.9  889.83   912.5  900.44
#Mann= 6 ,-1,0
       0      .1       0     280     .06       0  372.83    .045       0
   498.1      .1       0     690     .06       0     900      .1       0
Bank Sta=372.83,498.1
XS Rating Curve= 0 ,0
Exp/Cntr(USF)=0,0
Exp/Cntr=0.3,0.1

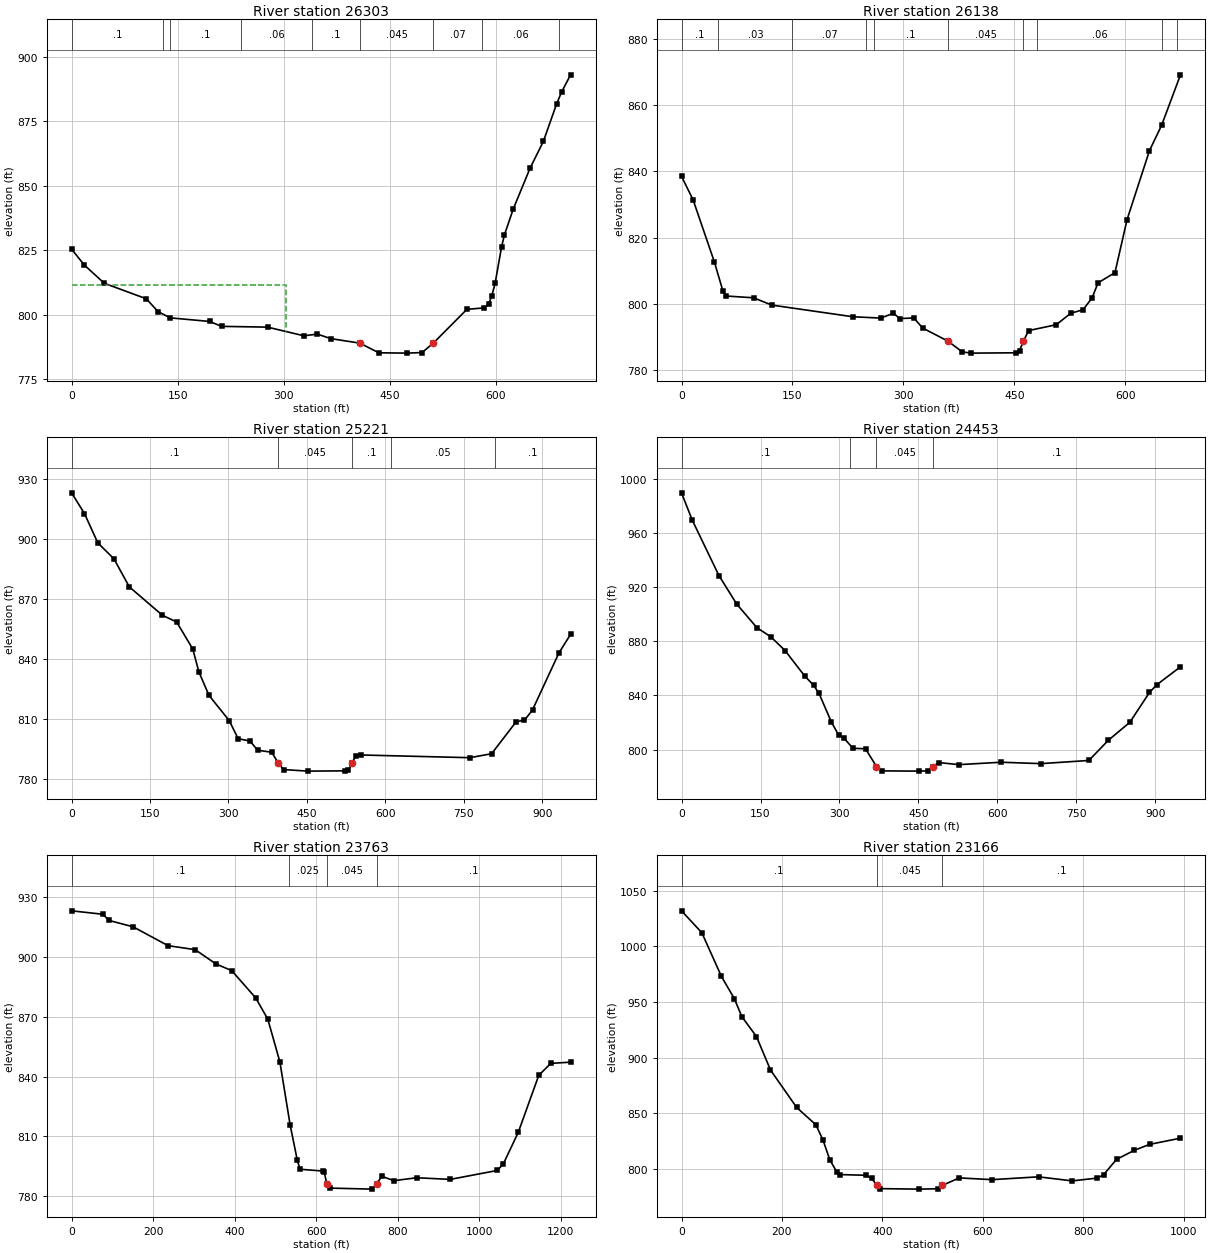
Type RM Length L Ch R = 1 ,26303   ,167.4,165.4,166.7
XS GIS Cut Line= 3
1663017.64443141534410.1210726021662947.96790729534414.488642251
1662433.26787428534787.660949207
#Sta/Elev= 30
       0  825.39      18  819.24    46.2  812.18   105.7  806.15   122.1  801.21
   139.3  798.77   195.2  797.37     212  795.47   277.1  795.17   328.4  791.82
   347.6  792.46   366.4  790.72  407.47  788.97   434.5  785.22   474.7  785.09
   495.6  785.32  511.49788.9693     559  802.07   583.7  802.64   589.6  804.09
   594.3  807.37     599   812.3   608.1  826.43   612.1  830.97   624.8  841.15
   648.3   856.8   667.1  867.16   685.9  881.77   692.9  886.32   705.6  893.01
#Mann= 9 ,-1,0
       0      .1       0  129.81     .07       0  139.81      .1       0
  239.81     .06       0  339.81      .1       0  407.47    .045       0
  511.49     .07       0  579.81     .06       0  689.81      .1       0
#XS Ineff= 2 , 0
          303.83  811.51
Permanent Ineff=
       F       F
Bank Sta=407.47,511.49
XS Rating Curve= 0 ,0
Exp/Cntr(USF)=0,0
Exp/Cntr=0.3,0.1

Type RM Length L Ch R = 1 ,26138   ,937.3,916.4,889.5
XS GIS Cut Line= 2
1662895.49093596534245.0998908471662353.92769148534647.289856551
#Sta/Elev= 30
       0  838.49    15.6  831.45    44.4  812.66      56  803.84    60.6  802.35
    97.4  801.82   121.9  799.62   231.9  796.08   269.4  795.69   286.5  797.15
   295.2  795.54     314  795.72   326.2  792.66  360.15788.7288   379.6  785.47
   391.6   785.1   452.9   785.2     457  785.87  462.34788.7294   469.2  791.91
   506.6  793.68   526.5  797.18   542.8  798.19   555.1  801.78   563.2  806.36
     586   809.4   602.4  825.45   632.7  846.28   649.1  853.93   674.6  869.18
#Mann= 10 ,-1,0
       0      .1       0      50     .03       0     150     .07       0
     250     .06       0     260      .1       0  360.15    .045       0
  462.34     .07       0     480     .06       0     650      .1       0
     670     .06       0
Bank Sta=360.15,462.34
XS Rating Curve= 0 ,0
Exp/Cntr(USF)=0,0
Exp/Cntr=0.3,0.1

Type RM Length L Ch R = 1 ,25221   ,772.4,767.9,744.2
XS GIS Cut Line= 2
1662293.64215176533353.0877609671661788.55896955534162.743716364
#Sta/Elev= 30
       0  923.23    24.6  912.83    50.1  898.21      81   890.2   110.3   876.2
   173.8  861.94   200.9  858.62   231.8  845.05   243.4  833.65   262.7  821.91
   301.4   809.3   318.5  800.22   341.3  799.05   355.6  794.47   382.6  793.45
  395.42788.0706   405.3  784.77   452.2     784     523  784.14   529.5  784.59
  536.39 788.073   543.7  791.63   553.3  792.08   761.6  790.72   803.3  792.71
   850.5  808.79     866  809.43   881.5  814.61   932.1  843.16   954.3  852.42
#Mann= 5 ,-1,0
       0      .1       0  395.42    .045       0  536.39      .1       0
     610     .05       0     810      .1       0
Bank Sta=395.42,536.39
XS Rating Curve= 0 ,0
Exp/Cntr(USF)=0,0
Exp/Cntr=0.3,0.1

Type RM Length L Ch R = 1 ,24453   ,690.5,690.2,651.6
XS GIS Cut Line= 2
1661511.90536724533005.3671782421661270.78525513533921.623604255
#Sta/Elev= 30
       0  989.65    20.2  969.63      71  928.57     105  907.38   143.2  889.99
   169.4  883.36   196.6  873.14   233.9  854.33   250.8  847.51     261  841.57
   284.7  820.24   298.3  810.76   308.5  808.43   325.5  800.93   349.4  800.57
  370.22787.4627   379.8  784.25   451.3  784.06     468  784.27  477.77787.4603
   488.3  790.41   526.5  788.85   607.1  790.63   682.3   789.6   773.6  791.94
   810.6  806.88   851.3  820.09   888.6  842.15   902.5  847.83   947.5  861.14
#Mann= 4 ,-1,0
       0      .1       0     320    .025       0  370.22    .045       0
  477.77      .1       0
Bank Sta=370.22,477.77
XS Rating Curve= 0 ,0
Exp/Cntr(USF)=0,0
Exp/Cntr=0.3,0.1

Type RM Length L Ch R = 1 ,23763   ,642.5,596.8,555.7
XS GIS Cut Line= 6
  1660687.247391532610.1066652541660701.67091858532708.666179419
1660716.03801584532806.8392114191660730.29192434532904.239279091
1660744.31945534533000.0930900131660811.01223534533827.712825835
#Sta/Elev= 30
       0   923.1    77.6  921.36    90.9  918.32   150.6  915.11   236.8  905.62
   303.1  903.63   354.8  896.39   392.9  893.12   451.9  879.39   481.5  868.74
   511.1  847.33   536.2  815.79   553.9  797.95   560.5  793.51   616.5  792.61
   619.8   792.1  626.22 786.282   632.9  784.06   738.3  783.54  748.51786.2872
   761.3  789.96   790.9  787.78   846.9  789.25   929.2  788.42  1044.6  792.91
  1059.4  796.18    1096  811.98  1146.4  840.62    1176  846.61  1224.4   847.2
#Mann= 4 ,-1,0
       0      .1       0  534.14    .025       0  626.22    .045       0
  748.51      .1       0
Bank Sta=626.22,748.51
XS Rating Curve= 0 ,0
Exp/Cntr(USF)=0,0
Exp/Cntr=0.3,0.1

Type RM Length L Ch R = 1 ,23166   ,945.1,883.2,834.8
XS GIS Cut Line= 2
1659907.60415191533230.2758775591660623.91419256533918.384735506
#Sta/Elev= 30
       0 1032.02    40.5 1012.31    79.5  973.05   105.1  953.17   120.2  936.89
   149.2  919.08   177.1  889.04   229.2   855.4   267.5   839.8   281.6  826.15
   295.2  808.41   308.9  797.57   316.2  795.08   366.5  794.47   378.9  791.61
  388.92785.3311   395.3  782.47   472.6  782.02   511.1  782.35  519.06785.3251
   552.9  792.11   618.2  790.53   710.7  793.07     778  789.41   827.5  791.96
   840.1  794.87   866.1  808.79   901.6  816.92   932.1  822.24   993.3  827.79
#Mann= 3 ,-1,0
       0      .1       0  388.92    .045       0  519.06      .1       0
Bank Sta=388.92,519.06
XS Rating Curve= 0 ,0
Exp/Cntr(USF)=0,0
Exp/Cntr=0.3,0.1

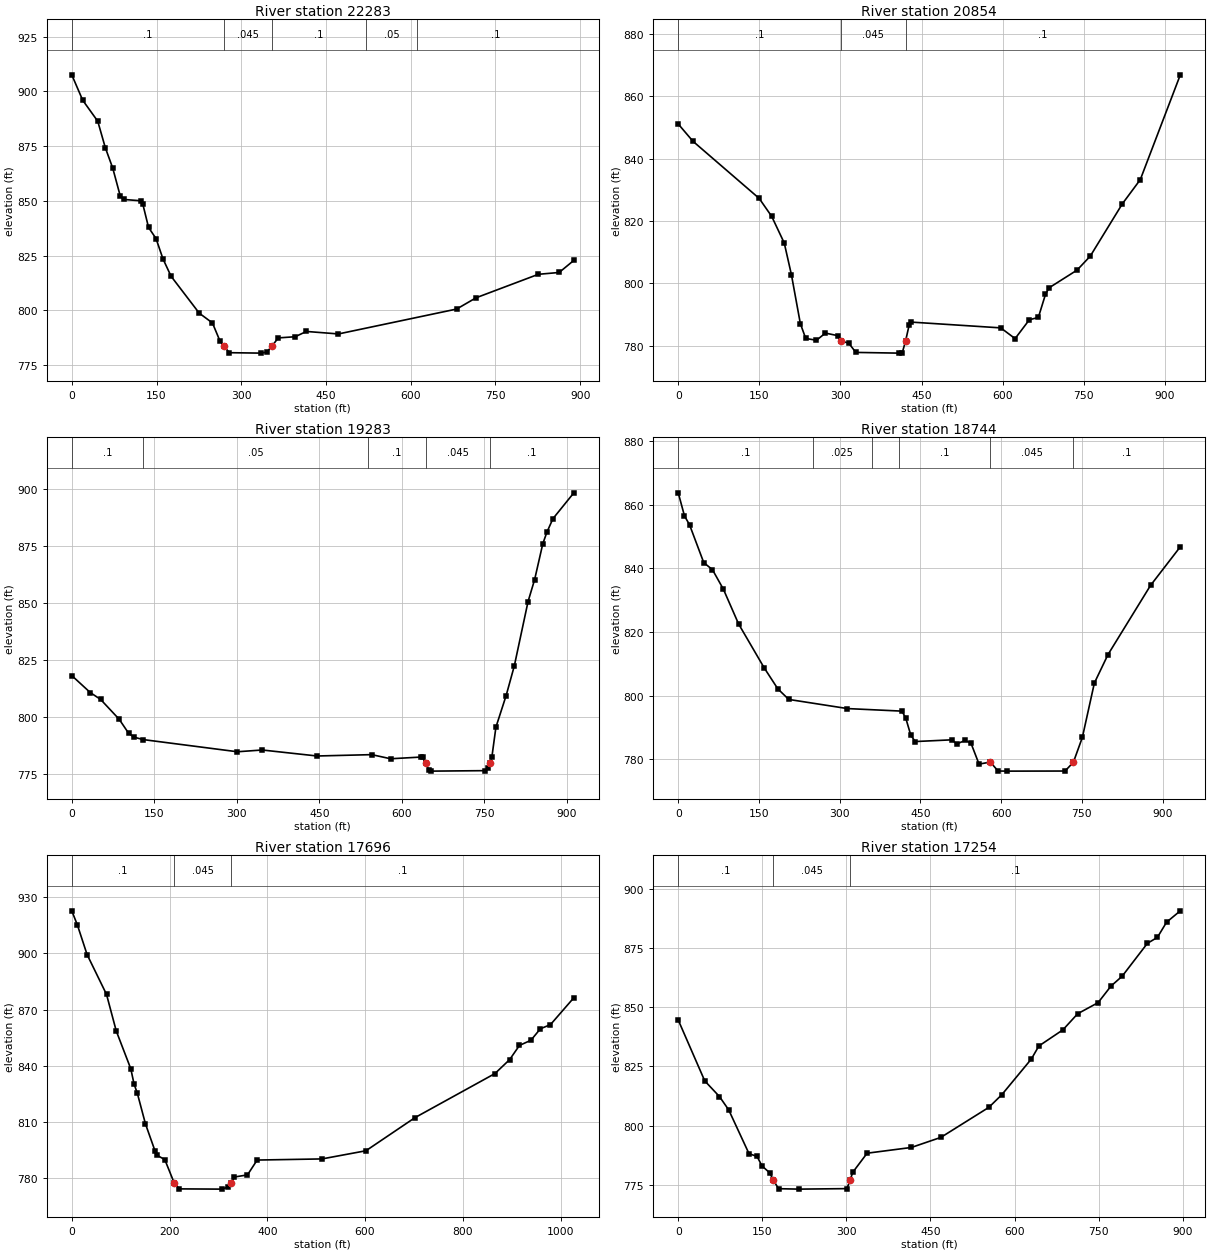
Type RM Length L Ch R = 1 ,22283   ,1408.9,1429.5,1410.1
XS GIS Cut Line= 6
1659845.48890392534441.9320698381660024.17785101534411.568941593
1660098.11766376534399.0043341671660196.70440884534382.252399176
1660270.64454967 534369.687791751660720.49673773534286.211182782
#Sta/Elev= 30
       0  907.62    19.4  895.99      46  886.41    59.3  874.37    72.6  864.91
    85.9  852.16    92.6  850.64   122.5  850.04   125.9  848.39   135.9  837.87
   149.2  832.75   161.4  823.52   175.8  815.54   225.7  798.66     249  794.21
   262.3  785.97  268.75783.7335     279   780.6   335.5   780.4   345.5  780.93
  354.74783.7359   365.5  787.36   395.4  787.89   415.4  790.31   472.1  789.17
   681.3  800.55   715.7   805.7   825.9  816.43   862.8  817.27   888.8   822.8
#Mann= 5 ,-1,0
       0      .1       0  268.75    .045       0  354.74      .1       0
  521.25     .05       0  611.25      .1       0
Bank Sta=268.75,354.74
XS Rating Curve= 0 ,0
Exp/Cntr(USF)=0,0
Exp/Cntr=0.3,0.1

Type RM Length L Ch R = 1 ,20854   ,1489.7,1570.5,1632.9
XS GIS Cut Line= 2
1660024.56218108535768.9541404961660945.13462252 535646.17340688
#Sta/Elev= 30
       0   851.1    27.3  845.56   149.7  827.27   172.9   821.5   196.1  812.97
   209.3  802.87   225.9  787.13   235.8   782.4   255.7  781.81   272.2  784.11
   295.4  783.28  301.53781.5067   315.2  780.93   328.5  777.92   407.9  777.69
   414.5  777.89   420.4781.5035   427.1  786.66   431.1  787.63   596.6  785.78
   623.1  782.34   649.5  788.39   666.1  789.12   679.3  796.52   685.9  798.61
   737.8   804.3   762.1  808.76   821.6  825.56   854.7  833.29   928.7  866.86
#Mann= 3 ,-1,0
       0      .1       0  301.53    .045       0   420.4      .1       0
Bank Sta=301.53,420.4
XS Rating Curve= 0 ,0
Exp/Cntr(USF)=0,0
Exp/Cntr=0.3,0.1

Type RM Length L Ch R = 1 ,19283   ,584.4,539.5,513.8
XS GIS Cut Line= 6
1659635.37777559536381.3291096691659684.01580167536468.302360922
1659729.96912184536556.237880588  1659775.560238536643.481144428
1659820.42825851536729.3392404171660060.68762051537189.096851096
#Sta/Elev= 30
       0  818.23    33.6  810.81    52.4  807.81    86.2  799.12   103.2  793.07
   112.9  791.31     130  790.23   301.1  784.91   346.3  785.68     446  783.06
   545.4  783.65   579.7  781.85   635.7   782.6   638.1  782.52  643.76779.7797
   649.1  777.02   652.7  776.44   751.7  776.65   756.4  777.69  760.55779.7819
   763.8  782.47   771.2  795.65   789.8   809.5   804.6  822.41   829.6  850.56
   841.6  860.22   856.4  875.83   863.8  880.88   874.9  886.85   912.9  898.15
#Mann= 5 ,-1,0
       0      .1       0  129.65     .05       0  537.93      .1       0
  643.76    .045       0  760.55      .1       0
Bank Sta=643.76,760.55
XS Rating Curve= 0 ,0
Exp/Cntr(USF)=0,0
Exp/Cntr=0.3,0.1

Type RM Length L Ch R = 1 ,18744   ,1058.5,1047.3,981.2
XS GIS Cut Line= 2
1658923.97320487536826.592823555 1659679.7649013537373.695767989
#Sta/Elev= 30
       0  863.77    11.6  856.52      21  853.74    47.4  841.85    63.6  839.62
    83.9  833.49   112.2  822.56   159.6  808.82   185.1  802.18   205.4  798.86
   314.5  795.99   415.7  795.19   422.7  793.05   432.1  787.67   440.3  785.63
   509.1  786.18   517.2  784.86   533.1  785.97   543.9  785.16     559  778.54
   580.1  779.19   594.2  776.38   610.7  776.34   718.8  776.37  734.31779.1343
     751  786.95   773.3  804.02   798.6  812.95   877.7  834.69     933  846.82
#Mann= 6 ,-1,0
       0      .1       0     250    .025       0     360     .05       0
     410      .1       0   580.1    .045       0  734.31      .1       0
Bank Sta=580.1,734.31
XS Rating Curve= 0 ,0
Exp/Cntr(USF)=0,0
Exp/Cntr=0.3,0.1

Type RM Length L Ch R = 1 ,17696   ,436.7,442.1,444
XS GIS Cut Line= 3
1658609.82960138537909.2806729721659143.75678659537832.929462623
 1659622.8067014537925.611277934
#Sta/Elev= 30
       0  922.58    11.5  915.04    31.3   899.3    71.1  878.06      91  858.59
   120.8   838.4   127.5  830.25   134.1  825.44   150.7  809.15   170.5  794.55
   173.9  792.46   190.4  790.04  209.79777.4734   220.3  774.46   306.4  774.33
   319.7  775.38  326.35777.4712   332.9   780.8   359.5   781.9   379.3  789.82
   511.9  790.42   601.9  794.77   702.3  812.42   865.9   835.9     896  843.35
     916  850.88   939.4  853.62   958.8  859.74   979.5  861.97  1027.3  876.28
#Mann= 3 ,-1,0
       0      .1       0  209.79    .045       0  326.35      .1       0
Bank Sta=209.79,326.35
XS Rating Curve= 0 ,0
Exp/Cntr(USF)=0,0
Exp/Cntr=0.3,0.1

Type RM Length L Ch R = 1 ,17254   ,620.8,624,628.6
XS GIS Cut Line= 3
1658669.12406545538329.1472257461659238.21349768538283.416824941
1659560.86688114538321.525492278
#Sta/Elev= 30
       0  844.57    47.3  818.91    73.6  812.29    90.1  806.66   126.3   788.2
   140.6  787.08   149.4  783.07   163.3  780.12  169.39777.1605     179  773.45
   215.2  773.27   300.8  773.48  306.98777.1582   311.2  780.31     337  788.42
     416  790.84   468.6  795.09   554.2  807.75   577.3  813.08   630.1  828.16
   643.4  833.62   686.3  840.43   712.7  847.23   749.1   851.9   772.2  858.91
     792  863.03   837.1  876.92   854.9  879.42   871.3  885.83   895.8  890.62
#Mann= 3 ,-1,0
       0      .1       0  169.39    .045       0  306.98      .1       0
Bank Sta=169.39,306.98
XS Rating Curve= 0 ,0
Exp/Cntr(USF)=0,0
Exp/Cntr=0.3,0.1

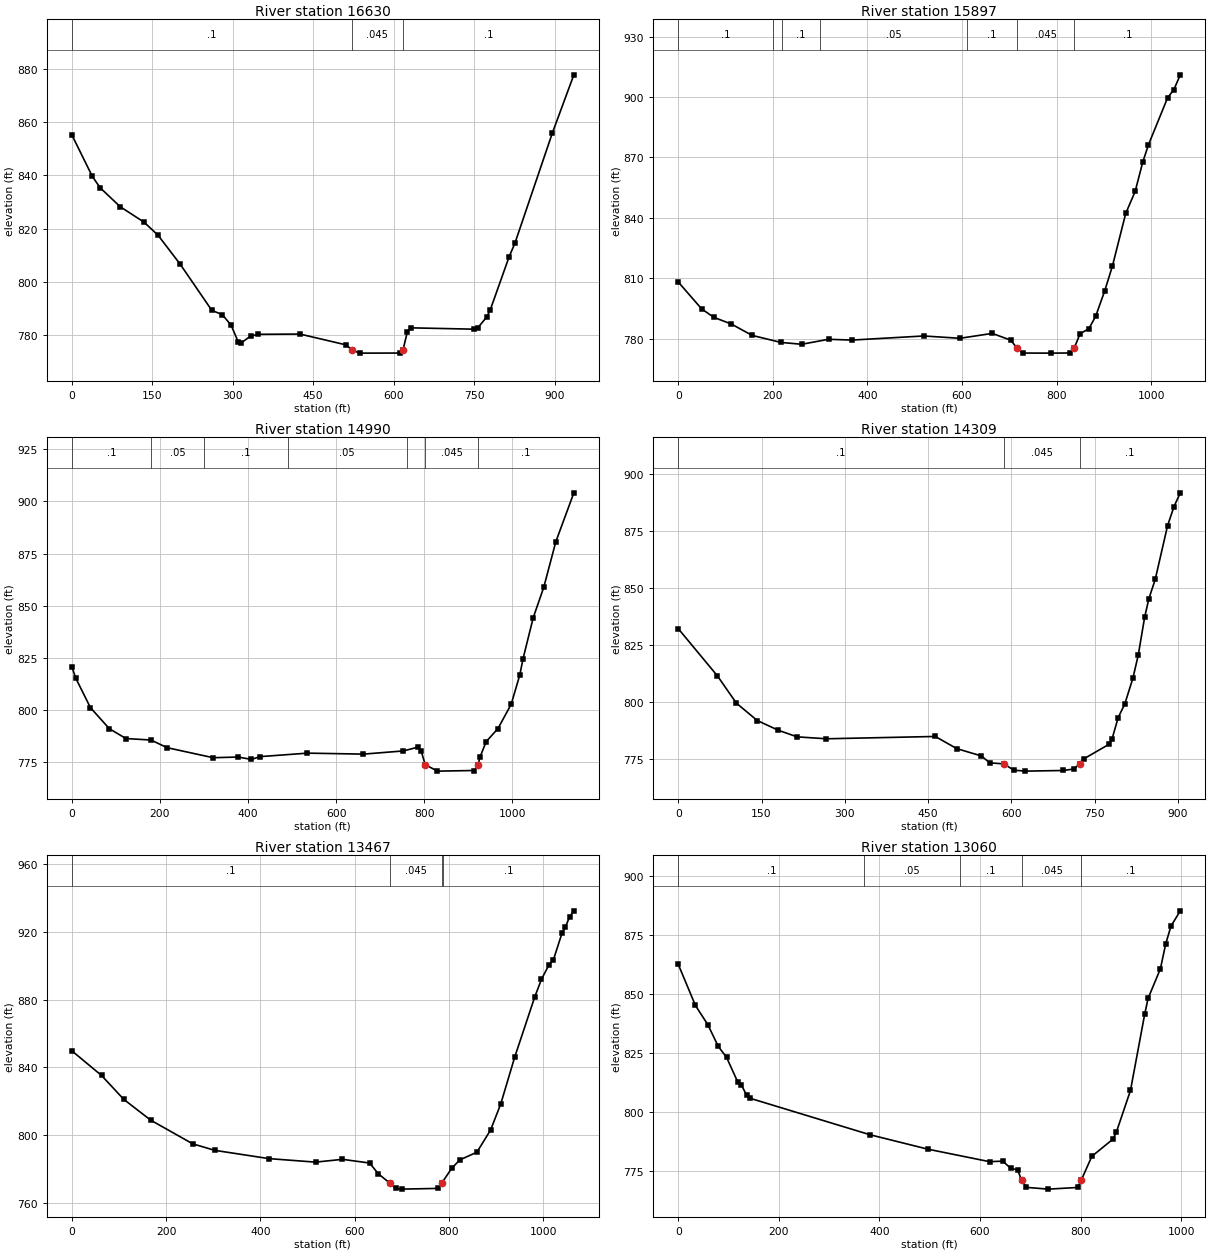
Type RM Length L Ch R = 1 ,16630   ,695.7,733,764.5
XS GIS Cut Line= 3
1658472.85973219 538790.660652391658698.37920376538912.257788129
1659377.47565571538937.409508571
#Sta/Elev= 30
       0  855.24    38.2  839.66    52.7  835.38    90.2  828.24     135  822.39
     161  817.48   202.1  806.64     261  789.34   280.7   787.7   297.1  783.73
   310.3  777.45   316.3  777.19   333.3  779.69   347.9  780.34   425.2  780.44
   511.8  776.35     522  774.43   536.8  773.28   612.3  773.31  617.41774.4695
   625.5  781.29     632  782.77     750  782.27   756.8  782.79   773.2  786.77
   779.8  789.39   815.2  809.46     826  814.56   895.6  855.81   935.8  877.73
#Mann= 3 ,-1,0
       0      .1       0     522    .045       0  617.41      .1       0
Bank Sta=522,617.41
XS Rating Curve= 0 ,0
Exp/Cntr(USF)=0,0
Exp/Cntr=0.3,0.1

Type RM Length L Ch R = 1 ,15897   ,858.6,907.6,948.5
XS GIS Cut Line= 2
1658349.61270923539168.7374683921659214.03545317539784.644444413
#Sta/Elev= 30
       0  808.16    49.6  794.76    75.6  790.55   111.9  787.32   156.2  781.63
   216.7  778.15   260.9  777.21   317.8  779.69   367.2   779.3   518.8  781.34
   595.5  780.19   663.8  782.61   702.9  779.26   716.1  775.36   728.2  772.86
   788.3  772.82   828.9  772.89  837.36775.4391   849.4  782.43   868.2  784.99
   882.4   791.1   901.2  803.46   917.8  815.99     946  842.22   965.9   853.1
     982   867.7   994.1  876.32  1034.4  899.57  1047.8  903.74  1061.4  911.04
#Mann= 7 ,-1,0
       0      .1       0     200     .05       0     220      .1       0
     300     .05       0     610      .1       0   716.1    .045       0
  837.36      .1       0
Bank Sta=716.1,837.36
XS Rating Curve= 0 ,0
Exp/Cntr(USF)=0,0
Exp/Cntr=0.3,0.1

Type RM Length L Ch R = 1 ,14990   ,630,680.1,718.4
XS GIS Cut Line= 2
1658128.83296927539351.3523532551658361.24728174540467.152346754
#Sta/Elev= 30
       0  820.85     8.9  815.34    42.4  801.13    85.2  791.07   122.9  786.34
   179.8  785.62   216.7  781.94     321  777.15   377.6  777.47   407.7  776.34
   427.8  777.67   535.1  779.34   662.1  778.87   752.9   780.4   786.4  782.24
   793.1  780.37   802.3 773.832     830  770.72   913.7  771.02  922.21773.8297
   927.2  777.71   940.6  784.84   967.4  791.11   997.5  802.78  1017.1  816.88
  1024.3  824.53  1047.6  844.32  1071.3  858.75  1098.8  880.65  1139.7  904.08
#Mann= 7 ,-1,0
       0      .1       0     180     .05       0     300      .1       0
     490     .05       0     760      .1       0   802.3    .045       0
  922.21      .1       0
Bank Sta=802.3,922.21
XS Rating Curve= 0 ,0
Exp/Cntr(USF)=0,0
Exp/Cntr=0.3,0.1

Type RM Length L Ch R = 1 ,14309   ,806.6,842.5,881.9
XS GIS Cut Line= 2
1658012.22578155539406.863474549 1657566.3543737540193.426368382
#Sta/Elev= 30
       0  832.19    70.7  811.38   104.6  799.48   142.3  791.81     180  787.56
     214  784.64   266.8  783.79   462.9  784.81   501.6  779.46   545.9  776.25
   561.1   773.2  586.15  772.78   604.4  769.99   625.1  769.58   693.5  769.86
   711.8  770.49  723.44 772.782   730.6  775.01   775.9   781.4     781  783.56
   792.2   793.1   804.1  799.07   818.7  810.39   828.3  820.48     840  837.38
   847.5  845.34   858.9  853.79   881.2  877.48   892.8  885.84   904.1  891.85
#Mann= 3 ,-1,0
       0      .1       0  586.15    .045       0  723.44      .1       0
Bank Sta=586.15,723.44
XS Rating Curve= 0 ,0
Exp/Cntr(USF)=0,0
Exp/Cntr=0.3,0.1

Type RM Length L Ch R = 1 ,13467   ,402.9,407.4,411.6
XS GIS Cut Line= 3
1657827.01765829539063.8854685171657296.54500896539290.250952498
1656852.96012116539493.751236077
#Sta/Elev= 30
       0  849.82    63.1  835.24   110.4  821.09   167.4  808.84   256.6  794.85
     303  791.03   418.1  786.13     517  784.05   574.1   785.7   631.8  783.52
   649.8  777.25  674.44771.6892   686.9  768.54   699.3  768.11     776  768.53
  784.72771.6896   805.7   780.4     823  785.37   859.2  789.92   888.1  802.95
   909.7  818.33   939.3     846   981.9  881.62   996.2  892.06  1011.7  900.39
  1021.6  903.64  1039.7  919.32  1046.9  922.81  1055.6  928.88  1064.8  932.46
#Mann= 4 ,-1,0
       0      .1       0  674.44    .045       0  784.72     .08       0
  786.75      .1       0
Bank Sta=674.44,784.72
XS Rating Curve= 0 ,0
Exp/Cntr(USF)=0,0
Exp/Cntr=0.3,0.1

Type RM Length L Ch R = 1 ,13060   ,377.7,378.2,374.4
XS GIS Cut Line= 2
1657662.38821539538736.9131027661656727.20151895539086.750668919
#Sta/Elev= 30
       0  862.68    34.2  845.22    58.7  837.15    79.7  827.85    96.1  823.24
   118.2  812.87   125.3  811.71   135.8  807.25   142.8  805.91   381.6  790.44
   496.6  784.33   619.2  779.04   645.6  779.27   661.2  776.19   674.8  775.59
  682.74771.3198   692.6  768.15     736  767.41   794.3  768.11  801.75771.3185
   822.6  781.32   864.4  788.56   871.1  791.42   899.4  809.22   927.9  841.79
   934.4  848.21   958.9  860.77   969.4  871.25   979.9  878.85   998.5  885.33
#Mann= 5 ,-1,0
       0      .1       0     370     .05       0     560      .1       0
  682.74    .045       0  801.75      .1       0
Bank Sta=682.74,801.75
XS Rating Curve= 0 ,0
Exp/Cntr(USF)=0,0
Exp/Cntr=0.3,0.1

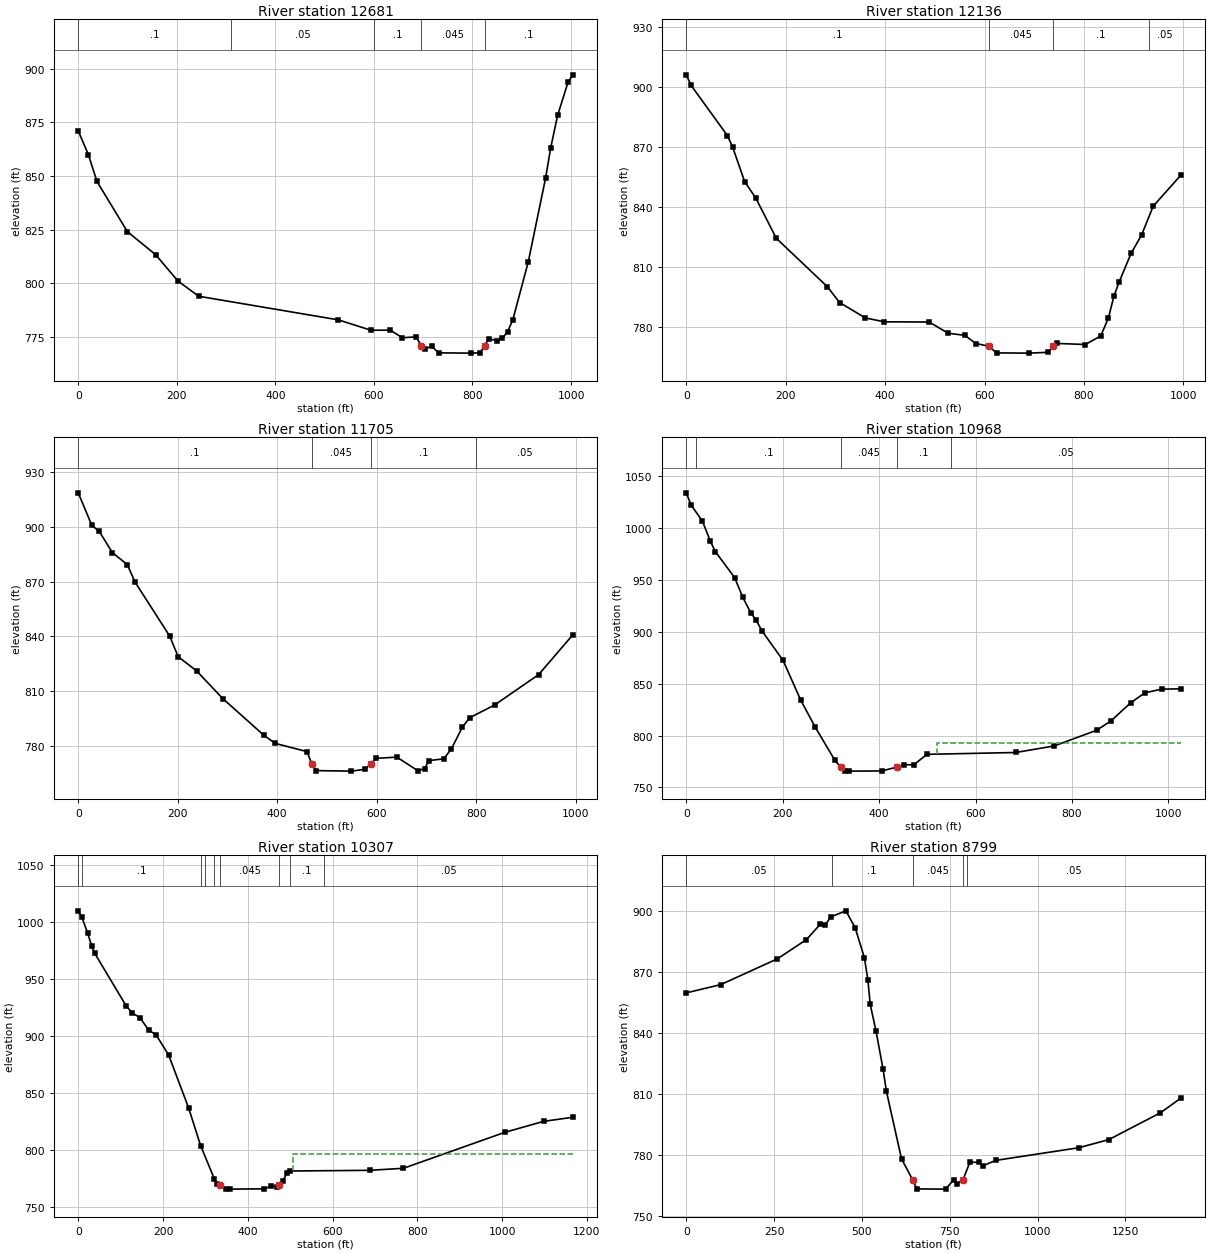
Type RM Length L Ch R = 1 ,12681   ,536.7,545.4,538.8
XS GIS Cut Line= 2
1657544.50540443538384.7890165731656604.49161012538735.388756073
#Sta/Elev= 30
       0  871.06    20.7  859.91    37.9  847.49    99.7  824.07     157  813.34
   202.5  800.99   244.5  793.94   528.1  782.91     594  778.08   633.2  778.13
   657.7  774.59   685.7  774.99  695.93770.9273   703.2  769.29   717.2  770.66
   731.2  767.54     796  767.41   815.3  767.55  824.56770.9273   832.8  774.04
   850.3   773.3   860.8  774.36   871.3  777.45   881.8   782.9   913.3  810.09
   948.3     849   958.8  863.23   972.8  878.33   993.8   893.7  1003.3  897.23
#Mann= 5 ,-1,0
       0      .1       0     310     .05       0     600      .1       0
  695.93    .045       0  824.56      .1       0
Bank Sta=695.93,824.56
XS Rating Curve= 0 ,0
Exp/Cntr(USF)=0,0
Exp/Cntr=0.3,0.1

Type RM Length L Ch R = 1 ,12136   ,433.9,431.2,414.2
XS GIS Cut Line= 2
1657386.98957944537902.0792303061656446.97578513538227.273191581
#Sta/Elev= 30
       0  906.28     9.8  900.95    82.7  875.83    93.1  870.18   117.4  852.78
   139.8  844.53   181.1  824.37     284  800.08   308.3  792.21   360.4  784.47
   398.6  782.54   488.8  782.43   526.7  776.83   560.3  775.75   582.6  771.66
  608.73 770.332   624.2  766.96   689.2  766.85   728.4  767.26  737.89770.3305
   745.7  771.71   802.7  771.17   833.7  775.43   849.2  784.37   860.3  795.34
   870.7  802.39     895  816.91   915.9  825.98   939.4  840.46   994.7  855.92
#Mann= 4 ,-1,0
       0      .1       0  608.73    .045       0  737.89      .1       0
     930     .05       0
Bank Sta=608.73,737.89
XS Rating Curve= 0 ,0
Exp/Cntr(USF)=0,0
Exp/Cntr=0.3,0.1

Type RM Length L Ch R = 1 ,11705   ,771.7,736.5,672.1
XS GIS Cut Line= 2
 1657135.7264328537453.9213024241656269.13533756 537940.95007099
#Sta/Elev= 30
       0  918.72    27.2   900.9    42.3  897.54    68.6  885.91    98.7  879.35
   113.8  869.93   183.7   840.2   200.9  828.83     238  821.03   290.6  805.85
   373.4  785.67     396  781.28     460  776.76   469.5 770.085   478.8  766.34
   549.1  766.06   576.7  767.08  588.23770.0992   599.2  773.05   640.6  773.75
   682.4  766.35   696.5  767.35   704.6  771.84   734.7  772.79   749.9  778.06
   772.4  790.22   787.4  795.41   837.1  802.32   925.8  819.03   994.1  840.74
#Mann= 4 ,-1,0
       0      .1       0   469.5    .045       0  588.23      .1       0
     800     .05       0
Bank Sta=469.5,588.23
XS Rating Curve= 0 ,0
Exp/Cntr(USF)=0,0
Exp/Cntr=0.3,0.1

Type RM Length L Ch R = 1 ,10968   ,683.9,661.3,629.9
XS GIS Cut Line= 2
1656245.44087154536863.7373725531656035.08102784537867.519670206
#Sta/Elev= 30
       0 1034.15     9.7 1022.51    33.2 1007.07    49.9  987.46    60.3  977.46
   100.2  952.41     117  933.57   133.7  918.45   144.3  911.72   157.2  900.84
   200.8  872.48   237.6  833.97   267.8  807.87     308  776.34  320.37769.5357
   328.2  766.25   338.2  765.72   405.3  765.89  436.41769.5341   452.2  771.83
   472.3  771.91   499.1  781.92   683.5  783.69   763.5  790.06   851.1   805.1
   881.2  814.22   921.5  831.54   951.6  841.31   985.9  844.77  1025.6  845.12
#Mann= 5 ,-1,0
       0     .06       0      20      .1       0  320.37    .045       0
  436.41      .1       0     550     .05       0
#XS Ineff= 2 , 0
                          519.86          793.16
Permanent Ineff=
       F       F
Bank Sta=320.37,436.41
XS Rating Curve= 0 ,0
Exp/Cntr(USF)=0,0
Exp/Cntr=0.3,0.1

Type RM Length L Ch R = 1 ,10307   ,1592.3,1508.4,1384.4
XS GIS Cut Line= 2
1655426.86669714536845.4452122311655680.67042161537984.132192257
#Sta/Elev= 30
       0 1010.03     8.3 1004.47    21.8   990.9    31.8   978.9    38.8  972.74
   112.5  926.77   126.7  920.48     146  915.94   166.3  905.03   183.1   901.3
   213.3  883.25   260.4   836.8   288.9  803.42   320.9  774.59   327.6  770.29
   334.7768.7182   347.8  765.84   357.9  765.38   438.6  765.65   455.4  767.93
   468.8  767.45  474.84768.7198   482.3  772.13   492.3  779.53   499.1  781.31
   687.3  781.91   767.2  783.69  1006.6  815.32  1097.9  824.93  1166.6  828.55
#Mann= 9 ,-1,0
       0     .06       0      10      .1       0     290    .025       0
     300      .1       0     320    .025       0   334.7    .045       0
  474.84     .05       0     500      .1       0     580     .05       0
#XS Ineff= 2 , 0
                          505.99          796.09
Permanent Ineff=
       F       F
Bank Sta=334.7,474.84
XS Rating Curve= 0 ,0
Exp/Cntr(USF)=0,0
Exp/Cntr=0.3,0.1

Type RM Length L Ch R = 1 ,8799    ,1506.2,1500.1,1467.7
XS GIS Cut Line= 6
1654127.49148168 538465.720938251654948.22638875538378.175509676
1655034.80233109538364.8609037551655126.58265933538341.409179002
1655221.14710276538314.5955843331655510.43491001538229.553103507
#Sta/Elev= 30
       0  859.83      98  863.88   259.6  876.62   342.1   886.1   381.7  893.69
   394.9  893.14   411.4  897.28   454.3  900.26   480.7  891.94   507.1  877.03
     517  866.15   523.6  854.16   540.1  840.99   559.9   822.5   569.8  811.22
   612.7  778.01  644.62767.6107   656.2  763.18   738.1  763.08   761.1  767.62
     771  765.75  787.65  767.61   807.3  776.38   833.8  776.26   843.3  774.48
   880.7  777.24  1117.4  783.48    1203   787.5    1350  800.73  1407.5  807.89
#Mann= 5 ,-1,0
       0     .05       0  414.14      .1       0  644.62    .045       0
  787.65      .1       0  800.39     .05       0
Bank Sta=644.62,787.65
XS Rating Curve= 0 ,0
Exp/Cntr(USF)=0,0
Exp/Cntr=0.3,0.1

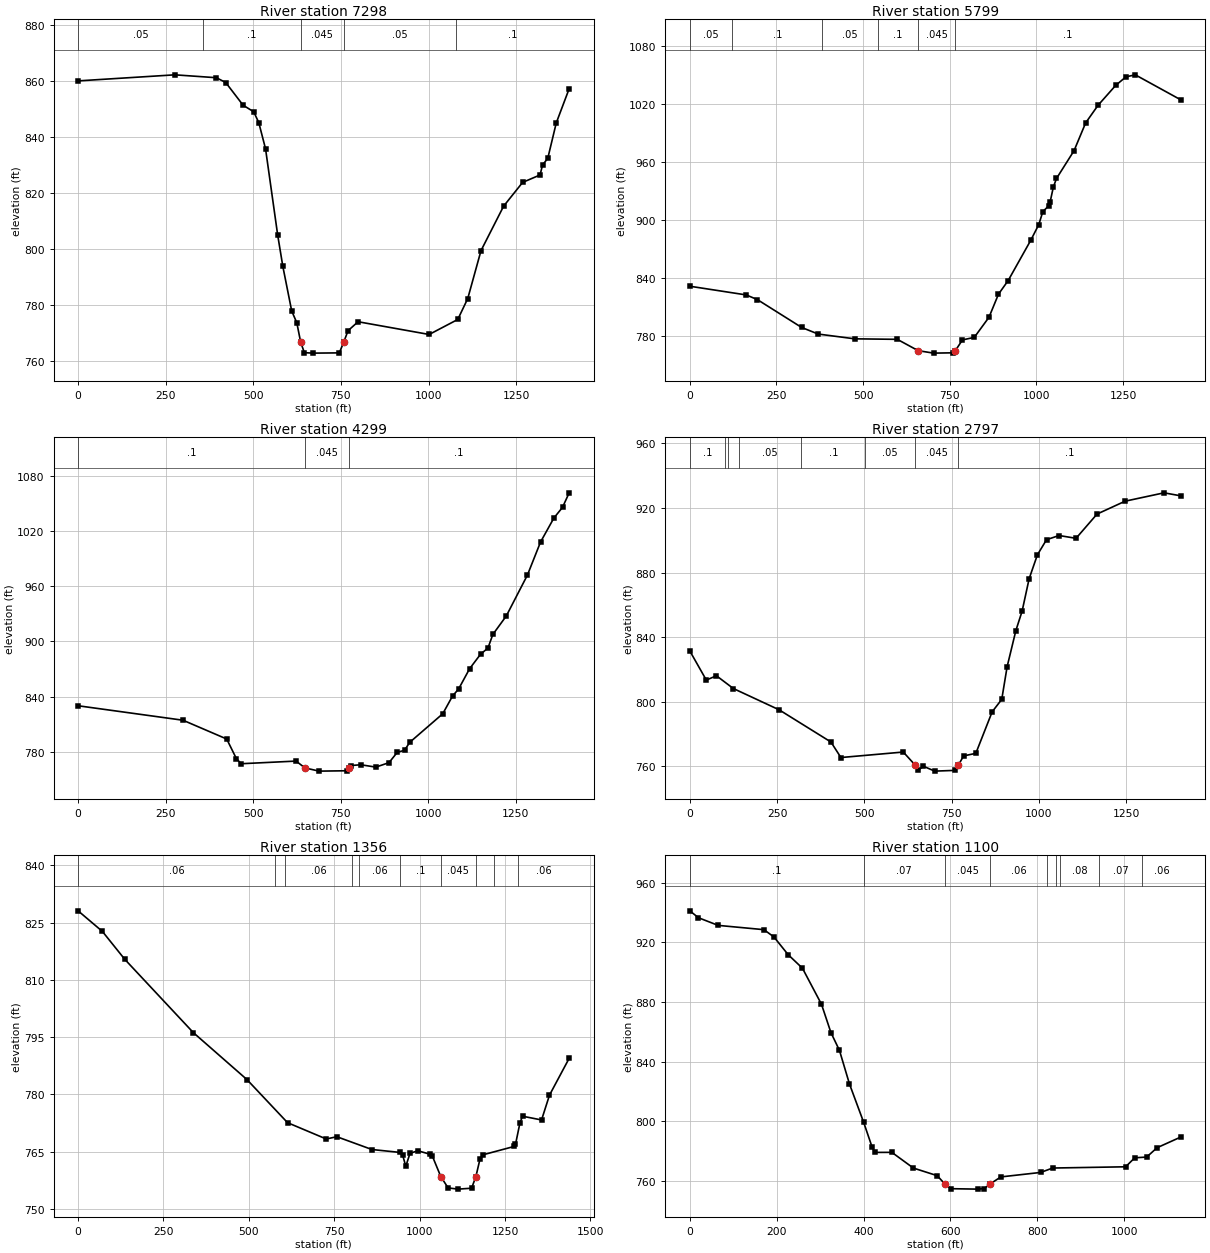
Type RM Length L Ch R = 1 ,7298    ,1426.6,1499.9,1556.5
XS GIS Cut Line= 6
1654484.04490243540131.5643913451654925.36094892539922.362709999
1655004.67312625539885.2371280941655072.88361976539853.958975419
1655164.99235943539815.0233577491655764.69325976539563.295514762
#Sta/Elev= 30
       0  859.93   276.2  862.09   394.6  861.06   421.3  859.35   470.8  851.27
   501.1  848.92   515.6  845.07     535  835.68   569.5  805.04   584.3  793.79
   609.6   777.9   624.1  773.73  635.17766.8238   645.7  763.04   670.7  762.88
   745.5  762.97  758.14766.8264   770.4  770.88     799  774.07  1001.9  769.53
  1083.5  774.88    1112  782.34  1149.8  799.41  1214.4  815.28  1268.6  823.74
  1318.4   826.4  1325.5  829.99  1340.3  832.28  1364.6  844.94  1401.4  857.14
#Mann= 5 ,-1,0
       0     .05       0  357.58      .1       0  635.17    .045       0
  758.14     .05       0 1077.25      .1       0
Bank Sta=635.17,758.14
XS Rating Curve= 0 ,0
Exp/Cntr(USF)=0,0
Exp/Cntr=0.3,0.1

Type RM Length L Ch R = 1 ,5799    ,1432.9,1500,1564.9
XS GIS Cut Line= 6
1654755.26614475540757.6569711721654858.94277467540802.474794924
1655092.52104767540985.2434582561655233.62903318541100.368556082
1655289.06822675541150.9786910861655821.60817218541679.643972337
#Sta/Elev= 30
       0  831.55   162.9  822.55     195  817.72   322.8  788.92   370.5   782.1
   475.9  777.17   598.8  776.64  659.07764.9251   703.3  762.38     759   762.7
  766.29 764.924   786.8  776.04     821  778.68   863.4  799.47   890.8  823.35
   918.8  837.45     984  879.11  1007.2  895.36  1018.8  908.73  1035.2  914.46
  1039.9  918.82  1049.2  934.18  1058.2  942.95  1108.9  971.73  1142.3  1000.4
  1178.2 1018.66    1229 1039.19  1258.7 1048.05  1285.6 1050.12  1417.1 1024.23
#Mann= 6 ,-1,0
       0     .05       0  122.95      .1       0  382.02     .05       0
  543.82      .1       0  659.07    .045       0  766.29      .1       0
Bank Sta=659.07,766.29
XS Rating Curve= 0 ,0
Exp/Cntr(USF)=0,0
Exp/Cntr=0.3,0.1

Type RM Length L Ch R = 1 ,4299    ,1458.9,1501.4,1535.1
XS GIS Cut Line= 6
1654250.17037018540755.6743635831654214.78625458540849.133166179
1654146.70797868541035.4513630871654115.28186043541127.244814679
1654085.54340284541216.1823008361653775.39113601542074.771134838
#Sta/Elev= 30
       0  830.02   299.5  814.31   424.3  793.91   451.9  772.62   465.8  767.07
   622.4  769.94  647.57762.5375     688  759.03     768  759.43   774.3762.5345
   779.4  765.13   807.3  765.94     850  763.39   887.6  768.22   911.4  779.52
   931.9  781.62   946.9  790.32  1041.1  821.32    1069  840.55  1086.4  848.28
  1117.8  870.27  1149.2  886.06  1170.2  892.72  1184.1  907.46  1222.5  927.51
    1283  972.09  1320.2 1007.79  1358.6 1034.05    1383 1045.47    1402 1061.28
#Mann= 3 ,-1,0
       0      .1       0  647.57    .045       0   774.3      .1       0
Bank Sta=647.57,774.3
XS Rating Curve= 0 ,0
Exp/Cntr(USF)=0,0
Exp/Cntr=0.3,0.1

Type RM Length L Ch R = 1 ,2797    ,1454.1,1441.5,1419.1
XS GIS Cut Line= 6
1653291.57714301540210.4792597591652996.42911126540476.947558835
1652795.91868551 540639.594215171652713.35126534540696.081963092
1652334.16403159540941.2904621661652176.00161825541062.488054425
#Sta/Elev= 30
       0  831.49    47.3  813.46    76.3  816.13   124.7  808.24   255.9  795.07
   404.3  775.15   432.9  765.54   611.6  768.94  645.53760.8811   654.6  757.75
   669.5  760.12   701.7  757.13   760.9   757.6  769.46760.8855   784.5  766.56
   819.4  768.12   866.2  793.83   893.7  801.53   909.1  821.76   934.1  844.08
     952  856.11   972.1  876.14   995.8  890.93  1021.9  900.29  1057.9  902.89
  1106.5  901.16  1166.6  916.15  1247.1  924.13  1358.6   929.3  1406.8  927.43
#Mann= 8 ,-1,0
       0      .1       0     100     .05       0  110.36      .1       0
  140.36     .05       0   319.8      .1       0  502.32     .05       0
  645.53    .045       0  769.46      .1       0
Bank Sta=645.53,769.46
XS Rating Curve= 0 ,0
Exp/Cntr(USF)=0,0
Exp/Cntr=0.3,0.1

Type RM Length L Ch R = 1 ,1356    ,249.6,255.3,260.7
XS GIS Cut Line= 6
1652630.05589379538922.1409486171652406.89281739539092.341961613
  1652271.073527 539234.334856111652033.94589494539374.261857343
1651853.84416822539525.3551043651651578.35259415539881.287370613
#Sta/Elev= 30
       0  828.07    71.1  822.68   136.6  815.38   337.4  796.18   494.2   783.9
   613.2   772.6   726.5  768.33   757.6  768.92   860.3  765.57   941.7  764.82
   950.1  764.15   959.4  761.18   971.7  764.56   994.5  765.25  1029.5  764.36
  1037.4   763.8  1061.9 758.486  1083.3  755.52  1112.4   755.2    1152  755.44
 1164.65758.4857  1176.7   763.1  1186.2  764.21  1276.4  766.37  1280.6  766.91
  1293.7  772.57  1301.3  774.29  1356.9  773.31  1380.1  779.81  1437.7  789.45
#Mann= 10 ,-1,0
       0     .06       0  577.15      .1       0  607.15     .06       0
  802.49      .1       0  822.49     .06       0  942.49      .1       0
  1061.9    .045       0 1164.65      .1       0 1217.57     .07       0
 1287.57     .06       0
Bank Sta=1061.9,1164.65
XS Rating Curve= 0 ,0
Exp/Cntr(USF)=0,0
Exp/Cntr=0.3,0.1

Type RM Length L Ch R = 1 ,1100    ,1054.3,1014,973.2
XS GIS Cut Line= 4
1651727.61161516538854.7750177391651735.14075743 539301.11777663
1651529.58987367539513.7873057121651414.80171781539884.846693275
#Sta/Elev= 30
       0  941.16      20  936.52    65.2   931.4   170.7  928.52   193.7  923.63
   226.5  911.73   259.3  902.68   303.2  878.47   324.9  859.49   344.6  847.51
   367.6  825.03     400  799.52     420  782.42   426.6   779.1   465.2  779.14
   514.7  768.61   569.5  763.51  586.74758.0784   601.4  754.76   662.4  754.47
   678.2  754.89  692.28758.0789     716  762.66   807.9  765.67   835.4  768.62
  1003.4  769.45  1024.4  775.49  1051.8  775.97  1075.8  782.24  1130.6  789.44
#Mann= 9 ,-1,0
       0      .1       0     400     .07       0  586.74    .045       0
  692.28     .06       0  822.18     .07       0  842.18     .05       0
  852.18     .08       0  942.18     .07       0 1042.18     .06       0
Bank Sta=586.74,692.28
XS Rating Curve= 0 ,0
Exp/Cntr(USF)=0,0
Exp/Cntr=0.3,0.1