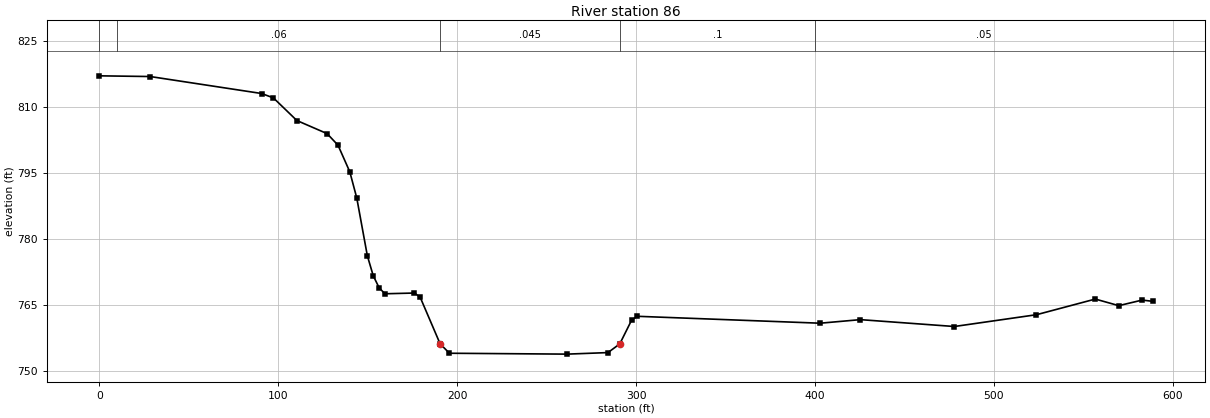
HEC-RAS study WhlingCk.prj: WhlingCk

--- WhlingCk.g01 (geometry) --- (continued)

Type RM Length L Ch R = 1 ,86      ,,,
XS GIS Cut Line= 2
1650641.13510439538944.5469964571650648.32664271539533.296120406
#Sta/Elev= 30
       0  817.05    28.4  816.89    90.7  813.03    97.3  812.03   110.4  806.89
   127.3  803.91   133.4  801.28     140  795.22   143.9  789.26   149.8  776.14
   153.1  771.59   156.4  768.86   159.6   767.5   176.1  767.67   179.3  766.74
  190.49  756.11   195.7  753.98   261.4  753.78   284.3  754.13   290.9  756.11
   297.5   761.5   300.7  762.38   402.9  760.81   425.4  761.62   477.9  760.06
   523.8  762.74   556.7   766.3   569.8   764.8   582.9  766.07 588.793  765.78
#Mann= 5 ,-1,0
       0     .05       0      10     .06       0  190.49    .045       0
   290.9      .1       0     400     .05       0
Bank Sta=190.49,290.9
XS Rating Curve= 0 ,0
Exp/Cntr(USF)=0,0
Exp/Cntr=0.3,0.1
LCMann Table=0

Chan Stop Cuts=-1
Use User Specified Reach Order=0
Composite Channel Slope=5